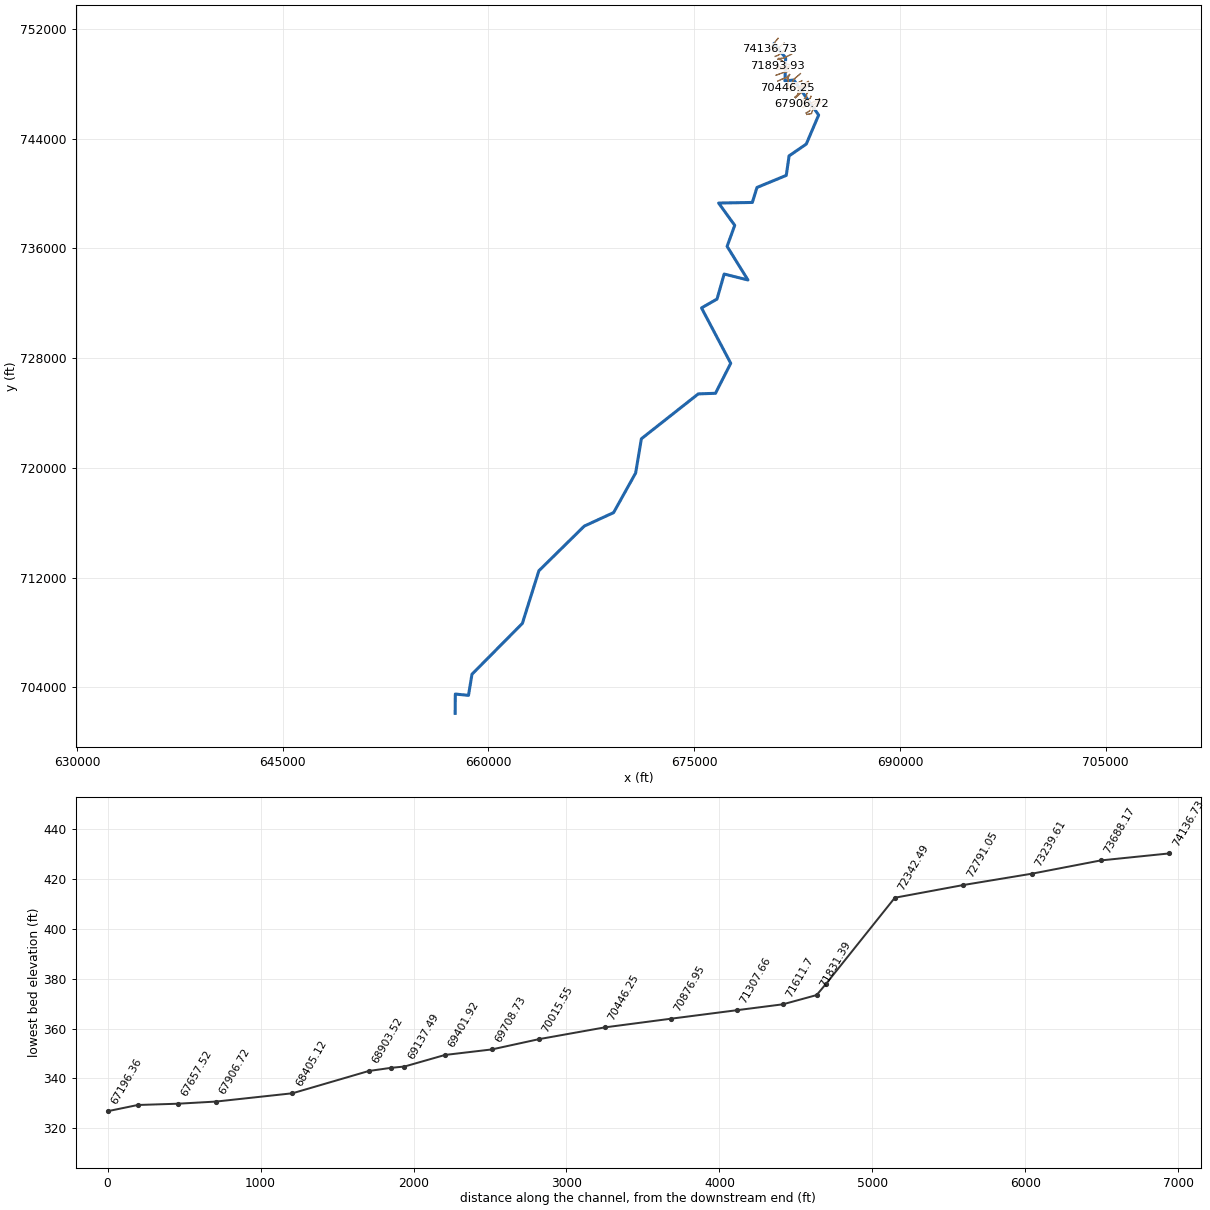
--- 3955_ras.prj (project) ---

Proj Title=3955
Current Plan=p01
Default Exp/Contr=0.3,0.1
English Units
Geom File=g01
Flow File=f01
Plan File=p01
Y Axis Title=Elevation
X Axis Title(PF)=Main Channel Distance
X Axis Title(XS)=Station
BEGIN DESCRIPTION:
RFD model 3955 exported to HEC-RAS
END DESCRIPTION:

--- 3955_ras.p01 (plan) ---

Plan Title=Plan 01
Program Version=4.10
Short Identifier=Plan 01
Geom File=g01
Flow File=f01
Subcritical Flow
Calc Critical at every XS
Secant Critical Depth

--- 3955_ras.f01 (steady flow) ---

Flow Title=Flow 01
Program Version=5.01
Number of Profiles= 6
Profile Names=10yr,25yr,50yr,100yr,100plus,500yr
River Rch & RM=3955,102,74136.73
  352.55 3495.3214740.4951195.6783757.8294795.45
River Rch & RM=3955,102,73688.17
  353.35 3500.0714752.3351213.1983786.4894848.02
River Rch & RM=3955,102,73239.61
  356.39 3517.9914796.9551279.1983894.4695046.13
River Rch & RM=3955,102,72791.05
  358.07 3527.8814821.54 51315.583953.8795155.22
River Rch & RM=3955,102,72342.49
  361.13 3545.8614866.1751381.3384061.5795353.07
River Rch & RM=3955,102,71893.93
  362.01    355114878.9251400.1384092.3195409.56
River Rch & RM=3955,102,71831.39
  362.39 3553.2114884.3951408.1784105.4895433.78
River Rch & RM=3955,102, 71611.7
  362.45 3553.57 14885.351409.5284107.6895437.81
River Rch & RM=3955,102,71307.66
  381.25 3662.3815153.2251802.06 84749.996621.27
River Rch & RM=3955,102,70876.95
   383.2 3673.5615180.5751841.9184815.09 96741.7
River Rch & RM=3955,102,70446.25
  397.53  3754.915378.4752129.0385284.8397611.26
River Rch & RM=3955,102,70015.55
  399.91 3768.2815410.8652175.8185361.3797753.23
River Rch & RM=3955,102,69708.73
  402.26 3781.49 15442.852221.8985436.7597893.12
River Rch & RM=3955,102,69401.92
  404.62 3794.7215474.7352267.9185512.0598032.94
River Rch & RM=3955,102,69137.49
   405.3  3798.515483.8652281.0585533.5598072.88
River Rch & RM=3955,102, 69051.1
  406.52 3805.3215500.29 52304.785572.2398144.73
River Rch & RM=3955,102,68903.52
  406.59  3805.7 15501.252306.0185574.3898148.73
River Rch & RM=3955,102,68405.12
  408.56 3816.6915527.6652344.0785636.6598264.47
River Rch & RM=3955,102,67906.72
  411.11 3830.9215561.8952393.2485717.0998414.06
River Rch & RM=3955,102,67657.52
17097.9135406.3557983.3891803.06150192.9244171.7
River Rch & RM=3955,102,67393.95
17102.7735412.35 57989.291806.99150199.3244188.6
River Rch & RM=3955,102,67196.36
17111.6835423.3657999.8691814.18150211.1244219.6
River Rch & RM=3955,102,66582.18
17848.7336325.7958869.3392398.58151167.2  246743
River Rch & RM=3955,102,66104.64
17876.2536359.1858901.3392419.99151202.2246835.7
River Rch & RM=3955,102, 65627.1
18017.9936530.89 59065.792529.87151381.9247311.3
River Rch & RM=3955,102,65149.55
18052.8136572.9859105.9592556.76151425.9247427.8
River Rch & RM=3955,102,64672.01
18072.1236596.3259128.2592571.64151450.3247492.3
River Rch & RM=3955,102,64194.47
18104.48 36635.459165.5992596.56151491.1247600.2
River Rch & RM=3955,102,63716.93
18135.2136672.4659200.9992620.19151529.7247702.6
River Rch & RM=3955,102, 63330.7
18156.2636697.8659225.2392636.36151556.2247772.6
River Rch & RM=3955,102,62944.46
18872.0237554.1360038.7693176.83152440.4250118.9
River Rch & RM=3955,102,62494.25
19388.0338163.3360612.9393555.75153060.3  251769
River Rch & RM=3955,102,61874.84
19411.3638190.7260638.6693572.69  153088251842.8
River Rch & RM=3955,102,61012.39
19593.3938403.9660838.6993704.18153303.2252416.4
River Rch & RM=3955,102,60149.93
19792.1638635.8961055.7593846.59153536.1253038.2
River Rch & RM=3955,102,59756.92
19898.0838759.1161170.8493921.98153659.5253367.7
River Rch & RM=3955,102,59287.47
19916.4538780.4461190.7593935.02153680.8253424.6
River Rch & RM=3955,102,58944.45
19933.03 38799.761208.7393946.79153700.1  253476
River Rch & RM=3955,102,58549.81
20012.0338891.3661294.21 94002.7153791.5253720.5
River Rch & RM=3955,102,58071.02
20020.5738901.2561303.4494008.75153801.4  253747
River Rch & RM=3955,102,57450.32
   2117340221.9362526.0494803.68  155102257232.3
River Rch & RM=3955,102,56828.61
21204.2740257.3662558.6194824.73155136.4257324.9
River Rch & RM=3955,102, 56706.4
21218.7540273.7662573.6894834.47155152.3257367.7
River Rch & RM=3955,102, 55894.8
21299.6940365.3262657.79 94888.8155241.2257606.7
River Rch & RM=3955,102,54911.14
31331.7150815.2571798.41100561.7164522.3283017.6
River Rch & RM=3955,102,54043.15
31367.4250849.7971827.28100578.9164550.5283096.2
River Rch & RM=3955,102,53664.48
31415.2850896.0671865.93  100602164588.2283201.4
River Rch & RM=3955,102, 53203.9
31826.7951292.7172196.69100799.2164910.8284101.2
River Rch & RM=3955,102, 52705.5
31905.7251368.5672259.81100836.8164972.3284272.8
River Rch & RM=3955,102, 52207.1
31925.3251387.3972275.48100846.1164987.5284315.4
River Rch & RM=3955,102,51042.83
32159.91 51612.372462.41100957.2165169.4284823.2
River Rch & RM=3955,102,50228.93
32275.1651722.5672553.94101011.6165258.3285071.7
River Rch & RM=3955,102,49702.31
32294.9151741.44 72569.6101020.9165273.5285114.2
River Rch & RM=3955,102,48846.41
32518.2851954.6272746.31101125.7  165445285593.7
River Rch & RM=3955,102,48305.96
38358.1157334.1477111.66103670.1169607.7297326.2
River Rch & RM=3955,102,47262.73
38709.9857647.3177360.51103812.6169840.9297988.7
River Rch & RM=3955,102,45784.24
38890.5657807.5877487.65103885.3169959.9298326.9
River Rch & RM=3955,102,44876.52
39024.0957925.8977581.41103938.9170047.5298576.3
River Rch & RM=3955,102, 44221.2
39083.6157978.5977623.14103962.8170086.5298687.2
River Rch & RM=3955,102,43425.46
40411.8959146.0978543.91104486.8170943.9301130.5
River Rch & RM=3955,102,42452.53
40477.1259203.0278588.62104512.2170985.4301248.9
River Rch & RM=3955,102,41761.45
 40826.659507.4278827.38104647.5171206.7301880.8
River Rch & RM=3955,102,41033.76
   4086759542.5478854.88  104663171232.2301953.6
River Rch & RM=3955,102, 40246.4
 41099.859744.6479013.09104752.5171378.6  302372
River Rch & RM=3955,102,39748.61
 41149.859787.9879046.98104771.7  171410302461.6
River Rch & RM=3955,102,39350.49
42117.0560622.3979697.66105138.6172010.2304179.4
River Rch & RM=3955,102,38647.58
 42243.860731.16 79782.2105186.1  172088304402.3
River Rch & RM=3955,102,37944.68
42282.1760764.0679807.77105200.5172111.5304469.7
River Rch & RM=3955,102,37241.77
50462.0667525.09 84946.6108037.3176752.6317882.4
River Rch & RM=3955,102,36538.87
50720.6267731.2785099.91108120.4176888.6318278.7
River Rch & RM=3955,102,35835.96
   5142068286.8685512.11108343.4177253.4319342.9
River Rch & RM=3955,102,35133.06
51466.2368323.4885539.23108358.1177277.4319412.9
River Rch & RM=3955,102,34430.16
51712.1568518.0485683.23108435.8177404.6319784.2
River Rch & RM=3955,102,33509.81
52248.7968941.3185995.91108604.4177680.3  320590
River Rch & RM=3955,102,32589.47
52313.3668992.13 86033.4108624.5177713.4320686.5
River Rch & RM=3955,102,31669.12
52629.3669240.4386216.41  108723177874.5321157.6
River Rch & RM=3955,102,30748.78
52932.9169478.3886391.53108817.1178028.4321608.2
River Rch & RM=3955,102,29828.43
 53016.969544.1386439.89108843.1178070.9321732.5
River Rch & RM=3955,102,28848.99
53069.2369585.0786469.98108859.2178097.3321809.9
River Rch & RM=3955,102,27665.47
56871.0872517.2188606.94109998.4  179961327283.4
River Rch & RM=3955,102,27014.85
57531.25 73018.288968.49110189.5180273.8328205.4
River Rch & RM=3955,102,26834.47
57574.7373051.1388992.22110202.1180294.2328265.8
River Rch & RM=3955,102,26492.68
57639.9773100.4889027.78110220.8  180325328356.5
River Rch & RM=3955,102,25858.48
57700.7373146.4589060.89110238.3180353.6328440.8
River Rch & RM=3955,102,25141.31
58201.9973524.8489333.11110381.9180588.4329134.1
River Rch & RM=3955,102,24424.14
58247.6173559.2289357.82110394.9180609.7329196.9
River Rch & RM=3955,102,23706.97
58286.8673588.7989379.05110406.1  180628  329251
River Rch & RM=3955,102, 22989.8
58473.3773729.1689479.86110459.2180714.9329507.5
River Rch & RM=3955,102,22272.63
58509.98 73756.789499.63110469.6180731.9329557.8
River Rch & RM=3955,102,21555.46
58607.9973830.3889552.49110497.4180777.4329692.2
River Rch & RM=3955,102,20482.17
 58668.573875.8489585.11110514.5180805.5329775.2
River Rch & RM=3955,102,18841.75
58889.8374041.96 89704.2110577.2180907.9  330078
River Rch & RM=3955,102,17566.17
62034.2776375.5691365.85  111446182329.3  334290
River Rch & RM=3955,102,16073.05
62549.6276753.4391632.95111584.8182556.4334964.8
River Rch & RM=3955,102,13764.36
63141.9377186.1791938.19111743.1182815.5335735.2
River Rch & RM=3955,102,11014.67
 64943.178492.1692855.14  112217183590.8  338045
River Rch & RM=3955,102,8955.011
71320.1883002.8495975.26113809.6186196.3345852.1
River Rch & RM=3955,102,8685.577
71341.0683017.3395985.16113814.6186204.5345876.8
River Rch & RM=3955,102,7097.935
72180.7383598.8396382.27114015.2186532.6346864.7
River Rch & RM=3955,102,6354.238
72244.9483643.1796412.51114030.4186557.6346939.8
River Rch & RM=3955,102,4609.836
72947.3984127.3896742.24114196.6186829.4347759.1
River Rch & RM=3955,102,       0
73251.9784336.7396884.57114268.2186946.5348112.5
Boundary for River Rch & Prof#=3955,102,1
Up Type= 0
Dn Type= 2
Boundary for River Rch & Prof#=3955,102,2
Up Type= 0
Dn Type= 2
Boundary for River Rch & Prof#=3955,102,2
Up Type= 0
Dn Type= 2
Boundary for River Rch & Prof#=3955,102,2
Up Type= 0
Dn Type= 2
Boundary for River Rch & Prof#=3955,102,2
Up Type= 0
Dn Type= 2
Boundary for River Rch & Prof#=3955,102,2
Up Type= 0
Dn Type= 2

--- 3955_ras.g01 (geometry) ---

Geom Title=3955
Program Version=4.10

River Reach=3955,102
Reach XY= 30
680809.686793178 750915.89766477681665.936793178749894.369886979
681617.325682074748208.605998084682261.422904253748277.182386994
684071.717615187745721.422212169683169.460670739743603.974295482
681917.276064306742744.223138094 681711.54689759741321.480082527
679576.130230933740442.139804751679238.456619829 739350.12591587
676780.991342038739304.987026975 677953.73439762737679.118971407
677398.178842038736147.868971407678916.408008754733696.480082512
677185.505230933734131.375915855676662.935786515732305.855082512
675532.727453172731660.021749198677662.935786486727624.431471422
676550.088564277725436.931471422675296.833355933725393.528693631
671148.326411515722122.131124198670730.357661486719626.037374184
669123.586828172 716738.01654087666985.826411515715756.072096407
663676.292267978712498.509162411662472.950254083708662.788676262
658799.599559635704956.352044314658545.114605963703415.900655434
 657584.82814759703512.254822105657574.411480904702103.400655448

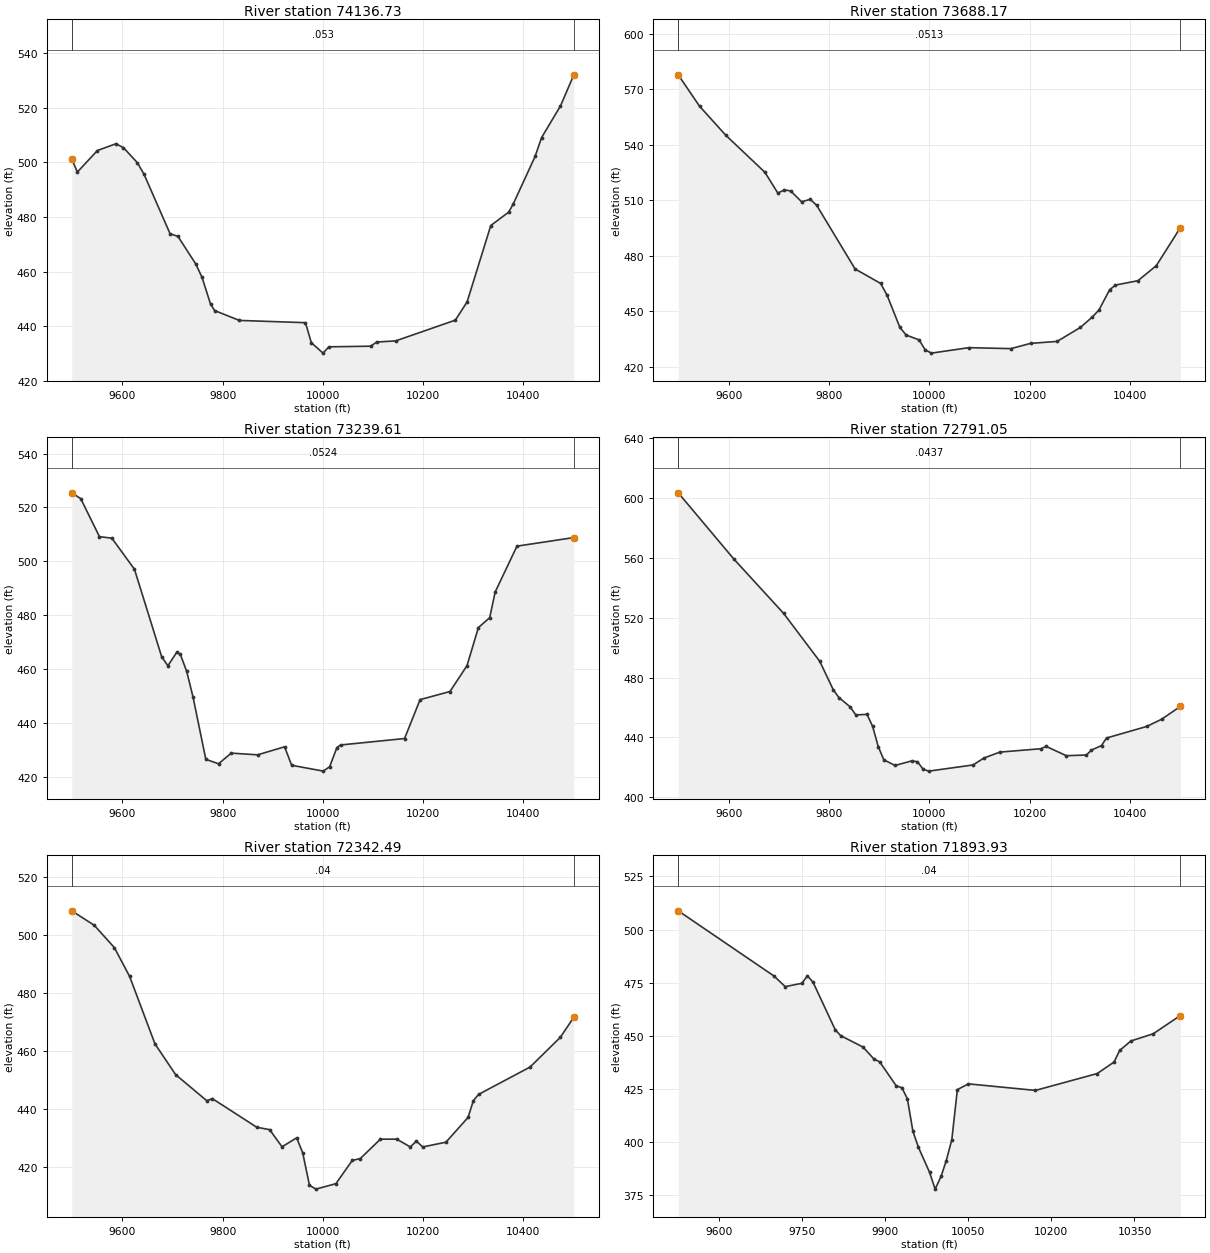
Type RM Length L Ch R = 1 ,74136.73,448.560500,448.560500,448.560500
XS GIS Cut Line= 6
681113.117914883751313.418837367680923.060623525751086.004873849
680768.404972463750847.474516115680703.454764107750762.192016872
680604.731306263750657.905181667680474.798430877750548.252410822
#Sta/Elev= 30
9499.051501.21299510.263496.43579550.217504.32319587.048506.79689602.189505.3649
9630.124499.82859643.442495.54399695.199  473.879711.021472.85279746.347462.8145
9758.961457.89369775.945448.07549784.188445.71189833.408442.1009 9965.41441.2712
9977.106433.933310000.47430.122210012.06432.430210095.33432.664210107.65434.1875
10145.23434.588910264.46442.203410287.93448.8742 10335.2476.8589 10370.9481.7569
   10380484.746210423.62502.145910436.46509.025510474.26520.654410500.94532.0448
#Mann= 3 , 0 , 0
9499.051   0.053       09499.051   0.053       010500.94   0.053       0
#XS Ineff= 2 , 0
       0                               0
Bank Sta=9499.051,10500.94
Exp/Cntr=0.3,0.1

Type RM Length L Ch R = 1 ,73688.17,448.560600,448.560600,448.560600
XS GIS Cut Line= 6
 681557.54160106750962.478035388 681335.16348984750777.964032322
 681184.52862753750658.647346275681110.153754468 750603.43916578
681053.006508526750566.400752299680743.958814867750381.593280756
#Sta/Elev= 30
 9499.01577.80229541.515560.83619593.763545.17339672.012 525.0899697.829513.8436
9710.737515.59879723.645514.97559745.221 509.139 9762.37 510.4829775.279507.2394
 9851.97472.81319902.998464.99269915.755458.63439941.269441.25629953.804437.0939
 9979.54434.4873 9991.87429.092410004.16427.308210078.92430.265610163.09429.7445
10202.06432.576910255.07433.638910301.67441.222910324.98446.744810338.45450.5694
10359.93461.573410371.58 464.11310416.39466.474410453.14474.627510500.96495.1142
#Mann= 3 , 0 , 0
 9499.01  0.0513       0 9499.01  0.0513       010500.96  0.0513       0
#XS Ineff= 2 , 0
       0                               0
Bank Sta=9499.01,10500.96
Exp/Cntr=0.3,0.1

Type RM Length L Ch R = 1 ,73239.61,448.560600,448.560600,448.560600
XS GIS Cut Line= 6
681719.452809016750569.195472546 681454.41978857750369.810604444
681261.080819929750187.467878966681190.764289171750130.316701235
681066.986920699750057.753489209680908.104004688749997.371730745
#Sta/Elev= 30
9499.029525.45089516.978523.28089554.236509.16439579.074508.58739624.148497.0421
9678.428464.52849690.847461.18089708.465466.17199715.727 465.3839728.422459.0458
9741.117449.45859766.507 426.4039791.897424.74679817.287428.70689869.904428.0703
 9923.75431.05899937.756 424.193   10001422.014610013.68423.685910028.09430.7745
10035.53431.7354 10163.1434.131610194.11 448.58910253.74 451.60610287.74461.2296
10310.41475.349910332.99479.047310343.87488.5825 10387.4505.6335 10500.9508.8225
#Mann= 3 , 0 , 0
9499.029  0.0524       09499.029  0.0524       0 10500.9  0.0524       0
#XS Ineff= 2 , 0
       0                               0
Bank Sta=9499.029,10500.9
Exp/Cntr=0.3,0.1

Type RM Length L Ch R = 1 ,72791.05,448.560600,448.560600,448.560600
XS GIS Cut Line= 6
682095.288122444750155.019879705 681810.97450923750021.603878853
681589.916664855 749910.82220745681527.253847154749884.881415425
681409.586712542749859.247126855681157.925843058749844.311748581
#Sta/Elev= 30
9499.009603.5916 9609.79559.38149709.206523.00679781.535490.85059808.622471.7215
9819.756466.6404 9842.14460.41469853.333455.06289875.717455.42129886.909447.4214
9898.102433.86889909.294425.02059931.678 421.2739965.255424.33719976.447423.7165
9987.639418.77769998.832417.4694 10087.3421.595910108.95426.215910140.87430.2008
10223.02432.447310233.15434.021510273.43 427.78810313.56428.2463 10323.6431.5232
10343.64434.597710353.65439.612610433.74447.329710463.78452.1998 10500.9460.7197
#Mann= 3 , 0 , 0
9499.009  0.0437       09499.009  0.0437       0 10500.9  0.0437       0
#XS Ineff= 2 , 0
       0                               0
Bank Sta=9499.009,10500.9
Exp/Cntr=0.3,0.1

Type RM Length L Ch R = 1 ,72342.49,448.560600,448.560600,448.560600
XS GIS Cut Line= 6
681969.745653739749386.321494228681663.135005067749448.675456341
681574.020437609749505.921246482681362.375554711749724.713260656
681234.047602003749772.703414656681098.038347507749788.762751194
#Sta/Elev= 30
9499.129508.39689543.984503.41749584.178495.68869614.534485.76829665.145462.4821
9706.339451.87959768.793442.83729779.349 443.6289868.251433.72269893.924432.8908
9918.634426.97669947.851430.06639959.936424.87019973.338413.71319986.213412.3719
10026.13414.258510058.72422.254610074.88422.936110114.93429.607710147.55429.6184
10174.47426.936710186.88428.956910199.29426.9219 10245.7428.571110289.75437.1097
10300.48442.951810310.87 445.06410413.43454.489210473.82464.739310500.85471.6788
#Mann= 3 , 0 , 0
9499.129    0.04       09499.129    0.04       010500.85    0.04       0
#XS Ineff= 2 , 0
       0                               0
Bank Sta=9499.129,10500.85
Exp/Cntr=0.3,0.1

Type RM Length L Ch R = 1 ,71893.93,62.535800,62.535800,62.535800
XS GIS Cut Line= 6
681947.851734092749222.922232375681799.613186236749224.200860735
681570.925419528749239.750078303681444.018221363749234.707131213
681402.705646486749235.984723093681046.359729381749286.295154291
#Sta/Elev= 30
9526.795508.7797 9699.77478.10899719.825473.15519749.909474.72299759.937478.2403
9769.964475.26219810.076452.88849820.103 450.0749860.195444.76129880.217439.0557
9890.229437.82189920.245426.49859930.245425.66549940.245420.45349950.245405.1624
9960.245397.5954 9980.28385.87769990.313377.9798   10001383.931410010.39391.3309
10020.41401.175210030.44424.747710050.46427.450110171.35424.377710282.84432.3122
10313.14 437.70110323.24443.141310343.44447.601610383.82450.983710432.73  459.57
#Mann= 3 , 0 , 0
9526.795    0.04       09526.795    0.04       010432.73    0.04       0
#XS Ineff= 2 , 0
       0                10085.72       0
Bank Sta=9526.795,10432.73
Exp/Cntr=0.3,0.1

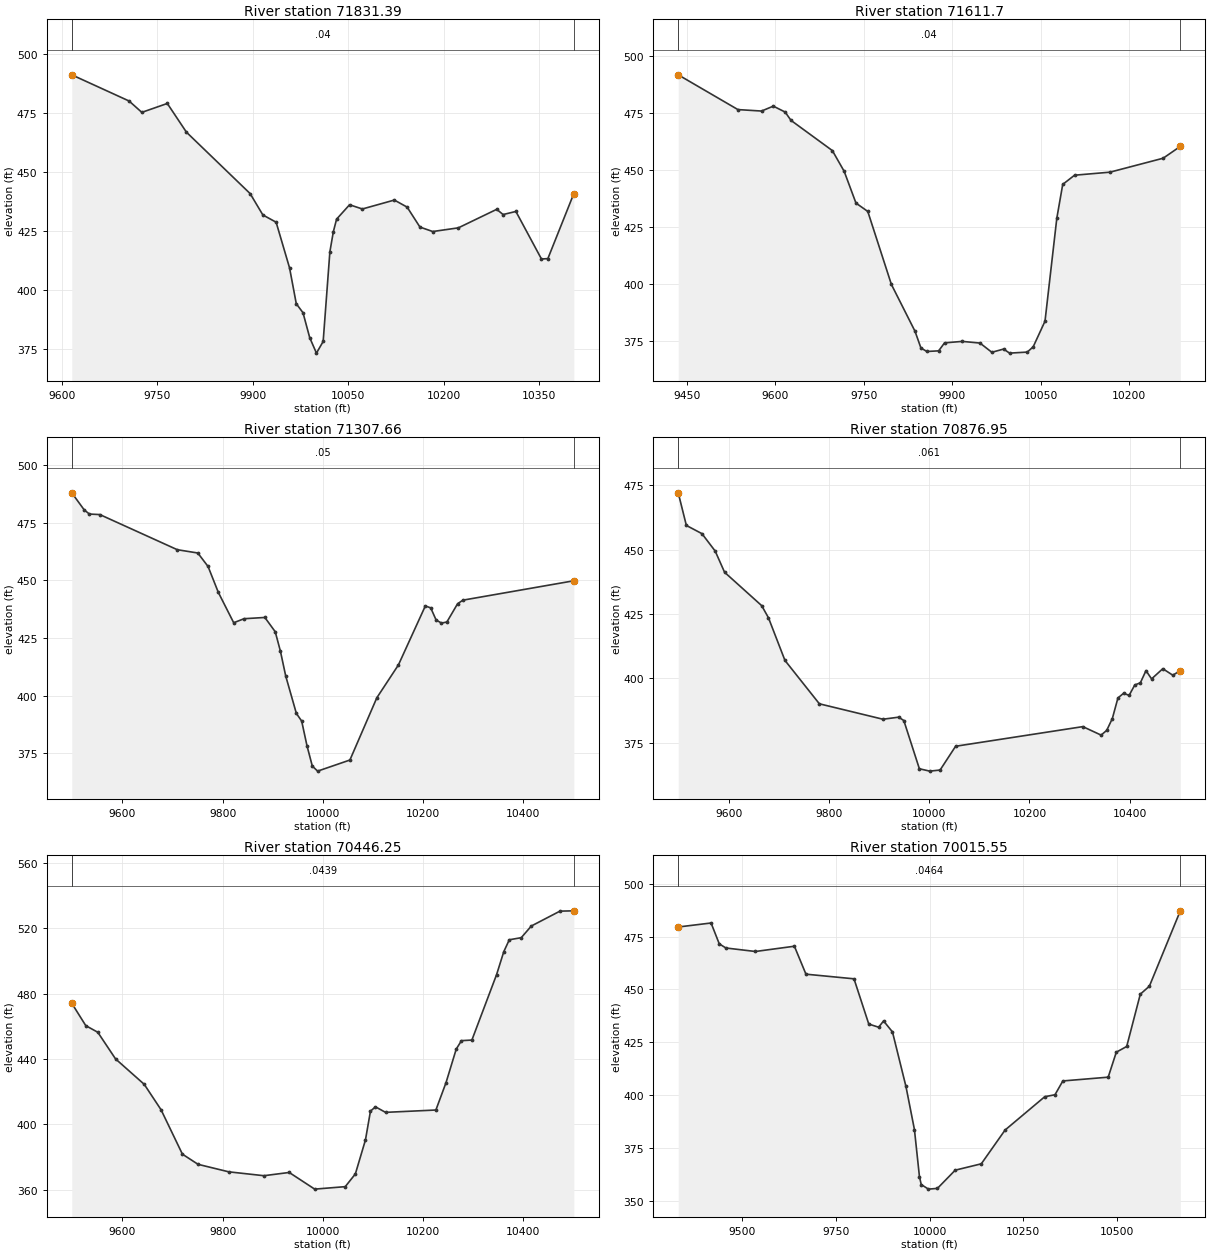
Type RM Length L Ch R = 1 ,71831.39,219.686100,219.686100,219.686100
XS GIS Cut Line= 4
681844.955778509749131.522122234681539.400222957749150.966566667
681429.678000778749188.466566667681064.400222957749228.744344443
#Sta/Elev= 30
9615.268491.33849705.406480.24299725.446475.42929765.527479.19999795.588467.0383
 9895.79441.0046 9915.83431.9477 9936.66428.87919957.795409.50919968.363394.3358
9978.931 390.5179989.499379.947110000.07373.398710010.64378.3467 10021.2416.3452
10026.68424.901910031.77430.183510052.16436.276110072.28434.484410122.59438.2697
10142.71435.272410162.83426.824310182.95424.931810223.19426.486310283.56434.3376
10293.62432.129510313.74433.434610353.98 413.28110364.04413.457110404.89441.0394
#Mann= 3 , 0 , 0
9615.268    0.04       09615.268    0.04       010404.89    0.04       0
#XS Ineff= 2 , 0
       0                 10084.1       0
Bank Sta=9615.268,10404.89
Exp/Cntr=0.3,0.1

Type RM Length L Ch R = 1 , 71611.7,304.047400,304.047400,304.047400
XS GIS Cut Line= 4
681856.066889644749067.980455592681446.344667464749071.452677801
681189.159368902749060.326797098681005.991300017 749053.19037883
#Sta/Elev= 30
9435.846491.64449536.916 476.4169576.917475.77479596.918477.92139616.919475.3373
9626.919471.67179696.922458.44889716.923449.37119736.923435.44389756.924431.7897
9796.925399.79469836.927 379.2939846.928371.97199856.938370.43159876.956370.7089
9886.966374.20599916.994374.85129947.022374.11579967.041370.08169987.059371.4923
9997.069369.7098 10027.1370.163510037.11372.479810057.12383.704510077.14428.8414
10087.15443.640310107.17447.662710167.22448.996510257.28455.105810286.32460.2916
#Mann= 3 , 0 , 0
9435.846    0.04       09435.846    0.04       010286.32    0.04       0
#XS Ineff= 2 , 0
       09921.721                       0
Bank Sta=9435.846,10286.32
Exp/Cntr=0.3,0.1

Type RM Length L Ch R = 1 ,71307.66,430.702800,430.702800,430.702800
XS GIS Cut Line= 6
 681918.73826036748929.989000026681822.008024849748901.617561302
681597.628135243748851.690203781681510.630031097748827.518925161
681191.560477288748704.374273595680965.831137868748626.157429214
#Sta/Elev= 30
9499.059487.86389523.797480.49799534.219478.66789555.061478.4459 9709.67463.2247
 9750.59461.7986 9771.05455.95379791.511444.74969822.201431.58639842.849433.3361
9884.364433.87839905.122427.67959915.501419.20369926.011408.52479947.235392.3289
9957.847 389.0069968.459378.31099979.071 369.5079989.683367.319310054.11372.1283
10107.87399.101810150.87413.301310204.63438.868710215.38438.030810226.13432.7847
10236.88431.436210247.63431.918610269.05439.841410279.67441.374410500.99449.7723
#Mann= 3 , 0 , 0
9499.059    0.05       09499.059    0.05       010500.99    0.05       0
#XS Ineff= 2 , 0
       0                               0
Bank Sta=9499.059,10500.99
Exp/Cntr=0.3,0.1

Type RM Length L Ch R = 1 ,70876.95,430.702700,430.702700,430.702700
XS GIS Cut Line= 6
681945.631315383748680.695523278681795.234786008748510.236808586
681702.132424554748437.202288866681633.236828466748408.059441597
681383.469243451748335.076509455681093.771713103 748198.25902829
#Sta/Elev= 30
 9499.12472.12769515.331459.44679546.401 456.2579572.893449.47079591.577441.2455
9665.614428.26619679.129 423.5519712.073406.95729780.739390.09289907.526384.0955
9938.912384.89459949.256383.59279980.289364.836210000.96363.915810021.62364.3333
10052.61373.588510306.45381.218410342.95 377.92110354.14 379.77310365.33384.3554
10376.51392.3677 10387.7394.166210398.89393.390710410.08397.411210421.27398.2545
10432.46402.991210443.65399.784710466.03403.740110485.94401.218110500.97402.9667
#Mann= 3 , 0 , 0
 9499.12   0.061       0 9499.12   0.061       010500.97   0.061       0
#XS Ineff= 2 , 0
       0                10152.77       0
Bank Sta=9499.12,10500.97
Exp/Cntr=0.3,0.1

Type RM Length L Ch R = 1 ,70446.25,430.702800,430.702800,430.702800
XS GIS Cut Line= 6
681954.518189548748647.981848261681881.922965659748531.847069516
681834.345379111 748403.18677526681860.454617248747980.553577364
681822.853604647747832.369609013681755.332444327747700.972468974
#Sta/Elev= 30
9499.136474.05979527.072460.38659551.058456.32759586.477440.0574 9643.73424.5045
9677.267408.96959719.892381.8215 9751.14375.60659812.328371.02729882.486368.6564
9932.956370.64139983.799360.454810044.75361.965710064.93369.738510085.06390.5044
10095.08408.1518 10105.1410.749110125.13407.3794 10225.6408.806410245.89425.6078
 10266.2446.059110276.61 451.19710297.43451.567810346.74491.608210361.05505.5798
10372.05512.866810395.92514.143510416.02521.276410473.15530.365910500.84530.5553
#Mann= 3 , 0 , 0
9499.136  0.0439       09499.136  0.0439       010500.84  0.0439       0
#XS Ineff= 2 , 0
       0                               0
Bank Sta=9499.136,10500.84
Exp/Cntr=0.3,0.1

Type RM Length L Ch R = 1 ,70015.55,306.812900,306.812900,306.812900
XS GIS Cut Line= 6
682741.637819201748735.944523916682308.304485887748366.500079453
 682188.86004141748185.944523901682123.582263649 747996.12970911
682047.193374723747855.759338722 681938.86004141747696.870449841
#Sta/Elev= 30
9329.909479.49629417.478481.39279439.259471.56099456.901 469.5929535.747467.9365
9639.635470.42289670.462457.22339798.567455.0353 9837.99 433.6729864.273432.1826
9877.414435.14279901.152429.95789937.122404.20379959.716383.87959973.093361.6389
9977.841357.90229997.073355.735210021.05356.083310068.46364.685210137.99367.6863
10201.44383.635610307.19399.369510334.52400.295810355.44406.811910476.38408.5968
10498.02420.396710525.71423.085610562.02447.787610586.22451.556710668.68487.1353
#Mann= 3 , 0 , 0
9329.909  0.0464       09329.909  0.0464       010668.68  0.0464       0
#XS Ineff= 2 , 0
       0                               0
Bank Sta=9329.909,10668.68
Exp/Cntr=0.3,0.1

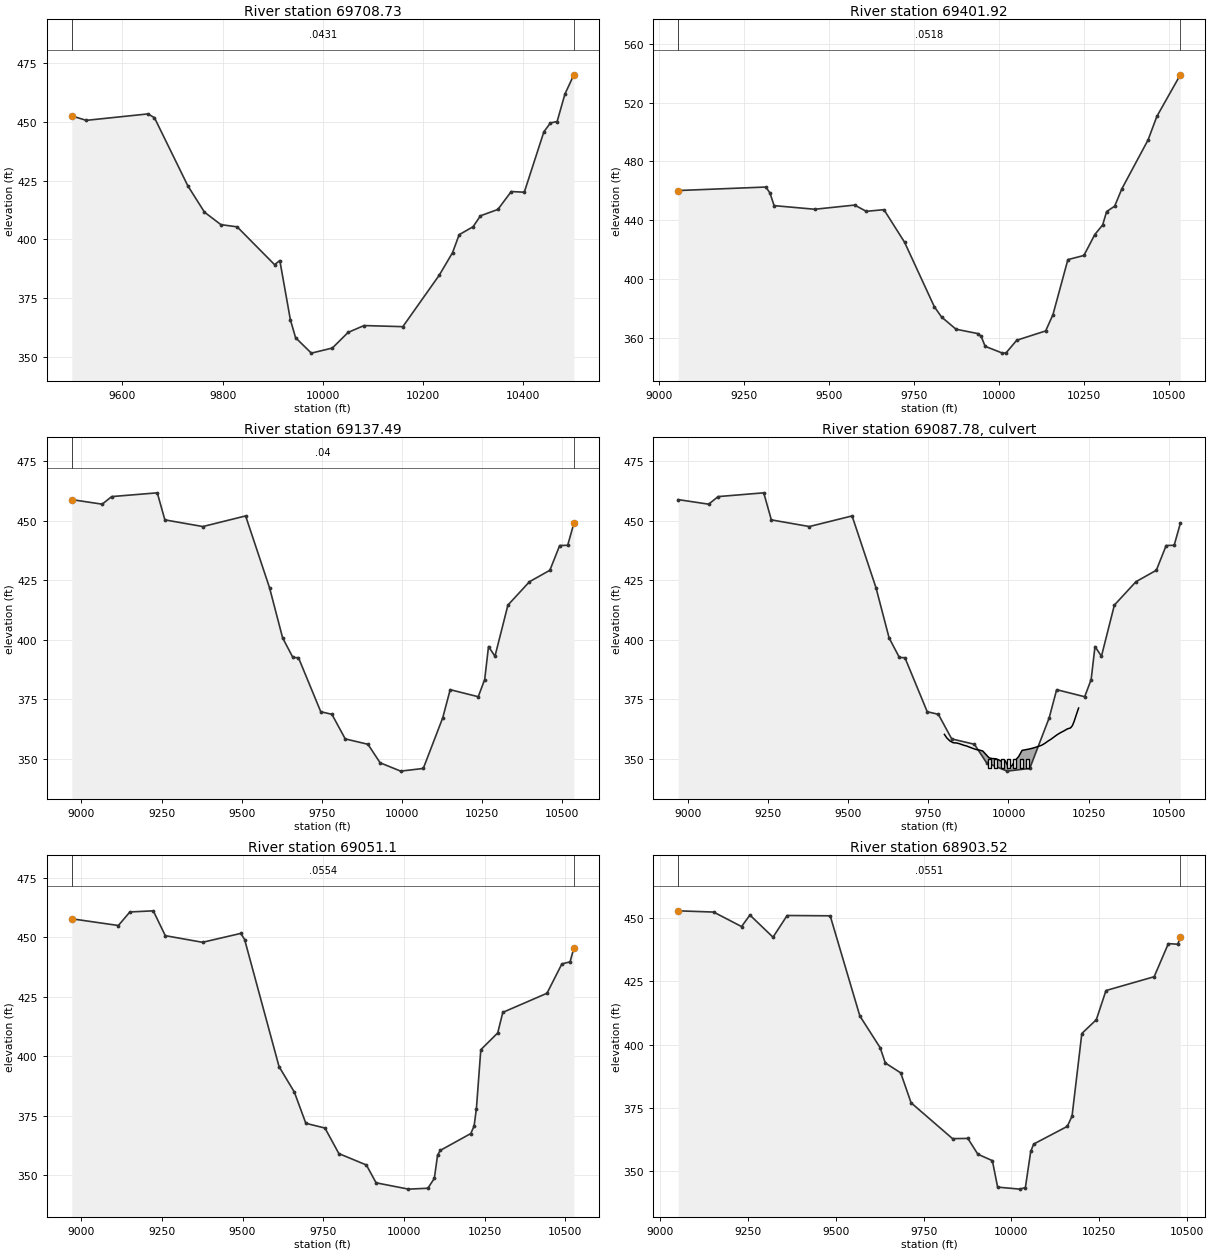
Type RM Length L Ch R = 1 ,69708.73,306.812800,306.812800,306.812800
XS GIS Cut Line= 6
682849.095107811748219.580607087682605.006465218748091.259708141
682317.103076661747991.187058655682235.690080383747952.377464591
 682134.33662118747870.530287655682003.599516722747719.143162344
#Sta/Elev= 30
9499.047452.4736 9528.12450.59429651.096453.32969664.044451.71779730.604422.7765
9763.884411.55359796.621406.25989829.087405.32019903.744389.24099914.224 390.998
9935.185365.91259945.666358.18649977.108351.635410018.96353.789910050.46360.4458
10082.25363.355110159.68362.8861 10232.4384.802410258.83394.334110272.04 401.985
 10299.9  405.3810314.57410.021410349.25412.706510375.96420.327410402.03420.0449
10441.13445.731810454.17449.491410467.55 450.09210483.14461.789110500.91469.9452
#Mann= 3 , 0 , 0
9499.047  0.0431       09499.047  0.0431       010500.91  0.0431       0
#XS Ineff= 2 , 0
       0                               0
Bank Sta=9499.047,10500.91
Exp/Cntr=0.3,0.1

Type RM Length L Ch R = 1 ,69401.92,264.435000,264.435000,264.435000
XS GIS Cut Line= 6
683306.994939106748171.786793389682815.080396503747853.025923923
 682661.70029369747781.808425039682400.370361596747696.570292711
682252.566462398747633.208877861682021.699186832747470.170287788
#Sta/Elev= 30
9057.232460.15469314.582462.53839326.722458.44939338.861449.87489458.405447.3989
 9575.31450.25329609.573445.99319661.465447.1169 9722.02424.94269809.342381.0751
9830.673374.02399873.184 365.6919936.412362.77769946.868360.95019958.716354.0656
10009.63349.414210020.11349.587210051.56358.194310136.45364.535910157.86375.6036
10201.77413.109310248.81415.924510280.78430.152110303.97436.766110315.56445.8468
10339.13449.487410360.26461.319210437.39494.676510463.14510.661110531.99538.9569
#Mann= 3 , 0 , 0
9057.232  0.0518       09057.232  0.0518       010531.99  0.0518       0
#XS Ineff= 2 , 0
       0                               0
Bank Sta=9057.232,10531.99
Exp/Cntr=0.3,0.1

Type RM Length L Ch R = 1 ,69137.49,86.383900,86.383900,86.383900
XS GIS Cut Line= 6
683340.119942159748115.888350732682777.360065013 747758.24655965
682619.373953879 747647.13544853682589.860065013747527.343781844
682549.929509461747213.107670754682349.919686288747037.655424029
#Sta/Elev= 30
 8969.86458.85649064.736 456.9359094.412460.12979236.594461.70729260.291450.3437
9378.777447.54179512.193452.00289586.769421.84099627.596400.77449659.675392.5295
9677.058392.4317 9746.59369.74289781.357368.65589822.916358.32199893.787 356.066
9931.682348.29479995.852344.785610066.42345.9138 10126.9367.119810150.38 379.006
10237.78376.043210257.94383.264210269.93397.140110290.03393.042810330.41414.5441
10397.72 424.368 10461.3429.176810491.88439.565410516.89439.670110536.08448.8529
#Mann= 3 , 0 , 0
 8969.86    0.04       0 8969.86    0.04       010536.08    0.04       0
#XS Ineff= 2 , 0
       0                               0
Bank Sta=8969.86,10536.08
Exp/Cntr=0.3,0.1

Type RM Length L Ch R = 2 ,69087.78,,,
Bridge Culvert--1,0,-1,-1, 0
Deck Dist Width WeirC Skew NumUp NumDn MinLoCord MaxHiCord MaxSubmerge Is_Ogee
25.192,36,2.6,0,56,56, , , 0.95, 0, 0,0,,
 9800.19 9807.41 9817.37 9817.66 9827.90 9838.14 9848.39 9858.63 9863.47 9868.88
 9879.12 9889.36 9899.61 9899.63 9909.62 9919.63 9929.64 9939.65 9945.64 9949.66
 9959.67 9969.68 9979.70 9986.02 9989.8910000.4210010.9410012.1110021.4610031.98
10042.5010044.3010053.0210059.7810063.3610073.3910083.4110093.4410103.4610113.49
10123.5110133.5410133.9110136.8110141.0910143.5510153.5610163.5710173.5810183.60
10193.5010193.6210199.3610204.6710215.7210218.84
  360.22  358.77  357.46  357.42  356.70  356.62  356.24  355.75  355.55  355.38
  354.83  354.32  353.85  353.85  353.62  353.26  351.80  350.36  350.18  350.06
  350.00  349.51  348.78  349.03  349.10  346.42  347.13  347.37  349.32  350.94
  353.51  353.56  353.77  353.95  354.04  354.35  354.76  355.18  355.65  356.45
  357.42  358.26  358.30  358.60  359.02  359.27  360.24  361.02  361.72  362.52
  362.93  362.93  363.89  365.63  370.10  371.29
                                                                                
                                                                                
                                                                                
                                                                                
                                                                                
                                                
 9800.19 9807.41 9817.37 9817.66 9827.90 9838.14 9848.39 9858.63 9863.47 9868.88
 9879.12 9889.36 9899.61 9899.63 9909.62 9919.63 9929.64 9939.65 9945.64 9949.66
 9959.67 9969.68 9979.70 9986.02 9989.8910000.4210010.9410012.1110021.4610031.98
10042.5010044.3010053.0210059.7810063.3610073.3910083.4110093.4410103.4610113.49
10123.5110133.5410133.9110136.8110141.0910143.5510153.5610163.5710173.5810183.60
10193.5010193.6210199.3610204.6710215.7210218.84
  360.22  358.77  357.46  357.42  356.70  356.62  356.24  355.75  355.55  355.38
  354.83  354.32  353.85  353.85  353.62  353.26  351.80  350.36  350.18  350.06
  350.00  349.51  348.78  349.03  349.10  346.42  347.13  347.37  349.32  350.94
  353.51  353.56  353.77  353.95  354.04  354.35  354.76  355.18  355.65  356.45
  357.42  358.26  358.30  358.60  359.02  359.27  360.24  361.02  361.72  362.52
  362.93  362.93  363.89  365.63  370.10  371.29
                                                                                
                                                                                
                                                                                
                                                                                
                                                                                
                                                
BR Coef=-1 , 0 , 0 ,, 0 ,,,0.8,-1,,0,
WSPro=,,,, 1 ,,,, 0 ,,,, 0 ,,,,-1 ,-1 ,-1 , 0 , 0 , 0 , 0 , 0
Multiple Barrel Culv=2,4,9.84,36,0.013,0.7,1,8,3,346,348,7,Culvert #1, 0, 25.192
 9940.96 9940.96 9960.64 9960.64 9980.32 9980.3210000.0010000.0010019.6810019.68
10039.3610039.3610059.0410059.04
Culvert Bottom n=0.013
BC Design=,, 0 ,, 0 ,,,,,,

Type RM Length L Ch R = 1 , 69051.1,147.581800,147.581800,147.581800
XS GIS Cut Line= 6
683366.826837392748070.820465023682691.943398356747640.653967053
682654.617009401747547.772022605682635.519787222747306.452578157
682609.478120565 747204.02202259682375.829257071747003.512905508
#Sta/Elev= 30
8970.618457.79179115.088454.97579150.664460.6635 9223.31461.1373 9260.52450.7077
9375.978447.92219494.564451.65649506.422449.0853 9613.15395.71669660.585385.0227
 9696.16371.91619755.454369.92419798.585359.1961 9883.85 354.4159913.944346.9262
10014.26344.275810074.44 344.64810094.51348.803510104.54358.577910113.11360.5528
10207.47367.612510217.79370.793110224.91378.110110238.54402.819610290.91409.8536
10306.72418.499610443.68426.518810489.82438.849210515.27439.719610526.94445.5278
#Mann= 3 , 0 , 0
8970.618  0.0554       08970.618  0.0554       010526.94  0.0554       0
#XS Ineff= 2 , 0
       0                               0
Bank Sta=8970.618,10526.94
Exp/Cntr=0.3,0.1

Type RM Length L Ch R = 1 ,68903.52,498.400600,498.400600,498.400600
XS GIS Cut Line= 6
683434.254427469747957.036406761683159.813999236747728.987294048
683042.061574638747615.009365559682804.068468451747362.278578445
682682.796781987747258.815495789682389.620990098746985.338752583
#Sta/Elev= 30
9052.009452.7673 9152.77452.28079232.112446.56619255.985451.09759321.609442.3665
9361.807450.92389484.334450.80339568.701411.29829626.612398.75959641.118392.7613
9684.896388.85479714.476377.04979832.391362.91029875.979362.99089904.465356.7637
9945.746354.22529960.699343.784810023.96342.992210039.65343.611610054.86 357.855
 10063.3360.778310158.97 367.75410172.45371.809110200.23404.374710241.49409.8242
10268.99421.326210406.07426.777410446.36439.827610473.21439.595210480.44442.3501
#Mann= 3 , 0 , 0
9052.009  0.0551       09052.009  0.0551       010480.44  0.0551       0
#XS Ineff= 2 , 0
       0                               0
Bank Sta=9052.009,10480.44
Exp/Cntr=0.3,0.1

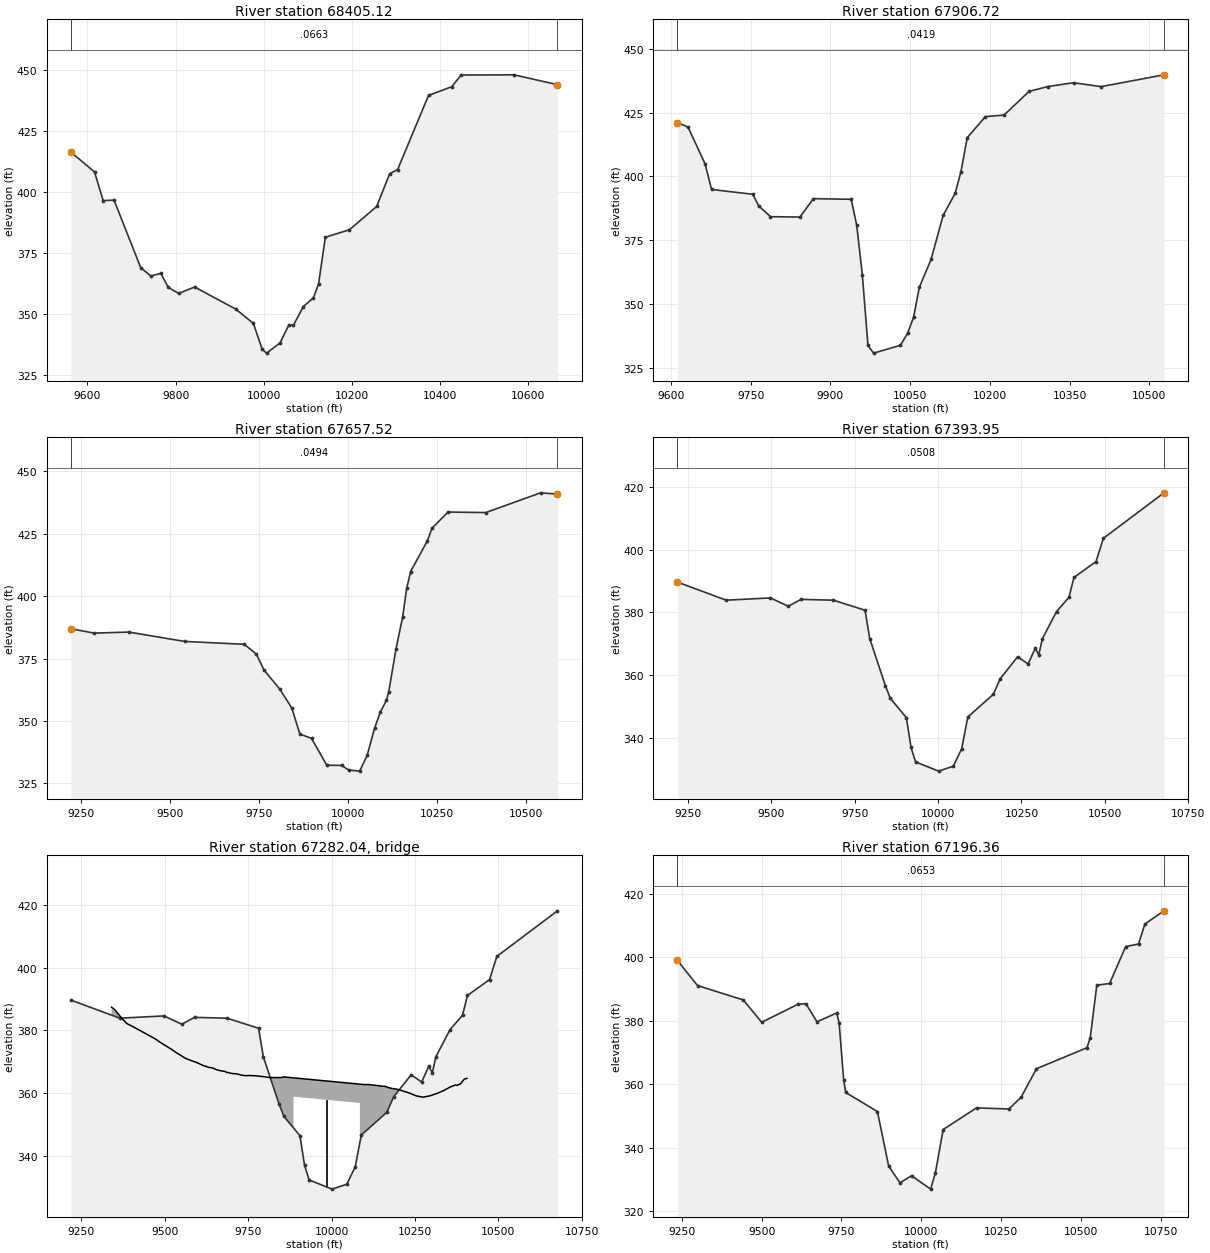
Type RM Length L Ch R = 1 ,68405.12,498.400700,498.400700,498.400700
XS GIS Cut Line= 6
683359.023314034747511.662196711683223.614708641747305.920510588
683192.528058796747209.311841775683176.388630356747066.864106743
683150.239997547747011.709520518682745.145263635 746640.58943927
#Sta/Elev= 30
9562.574416.28959615.951408.19339635.555396.47379660.264396.67499720.816369.0065
9743.612365.65319766.398366.67829783.024361.03519806.557 358.4829843.058361.1223
 9936.14352.09879976.373346.23459996.456335.568310006.48334.0753 10036.6338.2105
10056.86345.619810067.21345.4804 10089.6 353.12910112.61356.704610124.15362.3519
10139.59 381.48210194.25384.5564 10256.1394.085410285.48407.467210303.47409.1532
 10373.6439.496610426.16443.0555 10447.7447.847510567.59447.928410666.09443.8951
#Mann= 3 , 0 , 0
9562.574  0.0663       09562.574  0.0663       010666.09  0.0663       0
#XS Ineff= 2 , 0
       09857.841                       0
Bank Sta=9562.574,10666.09
Exp/Cntr=0.3,0.1

Type RM Length L Ch R = 1 ,67906.72,249.200300,249.200300,249.200300
XS GIS Cut Line= 6
683517.292707473747082.978174418683417.132451057746872.641635939
683369.544171393746797.557342216683268.574315459746761.550088167
683139.350543469746695.763045475682855.709190041 746506.84275414
#Sta/Elev= 30
9612.438421.08569632.351419.2917 9664.29404.93339676.654394.86329754.186392.9875
9765.262388.44699787.413384.21189842.793  384.069868.068 391.2719939.098391.0225
9949.656380.84179960.213361.41289970.771333.82659981.329330.763310031.98333.8274
10045.45338.595810056.46344.744310067.46 356.53810089.53367.496410112.19384.7142
10134.85393.364610145.68401.778210157.52 415.15110191.68423.398410226.88423.9985
 10273.8433.284910309.26435.189410357.55436.675910409.38435.151310527.51439.7706
#Mann= 3 , 0 , 0
9612.438  0.0419       09612.438  0.0419       010527.51  0.0419       0
#XS Ineff= 2 , 0
       09737.082                       0
Bank Sta=9612.438,10527.51
Exp/Cntr=0.3,0.1

Type RM Length L Ch R = 1 ,67657.52,263.569000,263.569000,263.569000
XS GIS Cut Line= 6
684130.570537418746894.201663432683559.574174255746607.466952801
683485.521854281746576.457597315683386.540290952746553.061322242
683317.732566535746524.337027252682914.609186739746276.826162398
#Sta/Elev= 30
 9220.43386.93669285.502385.19589383.324385.61749539.985 381.8689707.835380.7119
9741.406376.87649763.786370.37589808.546362.64269842.116355.08269864.388344.7728
9897.248343.00879940.232332.26539981.713332.190910002.04330.310910032.77329.8984
10053.79336.207110075.13 347.262 10090.6353.441210108.14358.318810114.55361.6976
10135.23379.002610153.67391.666710165.13403.111710176.12409.870410223.49422.2376
10236.29427.236910281.55433.701910387.97433.4989 10541.7441.4041 10589.3440.8815
#Mann= 3 , 0 , 0
 9220.43  0.0494       0 9220.43  0.0494       0 10589.3  0.0494       0
#XS Ineff= 2 , 0
       09862.649                       0
Bank Sta=9220.43,10589.3
Exp/Cntr=0.3,0.1

Type RM Length L Ch R = 1 ,67393.95,197.593300,197.593300,197.593300
XS GIS Cut Line= 6
684215.436566326746767.401832002683932.950342774746636.354198515
683712.117009461746484.965309635683492.672564954746276.631976306
683412.117009461 746023.85419853683151.013285398745865.307916626
#Sta/Elev= 30
9219.049 389.6619365.448383.89869497.505384.6238 9551.35381.97379589.405384.1646
9686.399383.89759781.264380.70019795.516371.61989842.534 356.5479857.058352.6051
9905.346346.41699919.135336.93539932.924332.302210001.87329.381510045.87330.9608
10070.81336.463310089.44346.651910165.59353.863510186.36358.839810238.34365.8241
10270.22363.574910291.47368.5832 10302.1366.469210312.72371.580610355.23380.2697
10392.56384.832510407.39391.141910473.53396.208410495.66403.624410677.14418.1438
#Mann= 3 , 0 , 0
9219.049  0.0508       09219.049  0.0508       010677.14  0.0508       0
#XS Ineff= 2 , 0
       09869.938        10123.33       0
Bank Sta=9219.049,10677.14
Exp/Cntr=0.3,0.1

Type RM Length L Ch R = 3 ,67282.04,,,
BEGIN DESCRIPTION:
END DESCRIPTION:
Bridge Culvert--1,0,-1,-1, 0
Deck Dist Width WeirC Skew NumUp NumDn MinLoCord MaxHiCord MaxSubmerge Is_Ogee
80.752050,36.089200,2.6,0, 56, 56, , , 0.95, 0, 0,0,,
 9340.66 9349.79 9371.01 9386.48 9405.77 9472.07 9484.30 9520.95 9533.13 9562.54
 9581.86 9594.04 9615.07 9632.58 9642.77 9654.95 9667.60 9679.31 9685.12 9691.49
 9703.68 9715.86 9728.04 9740.22 9752.46 9772.17 9801.66 9813.95 9850.85 9858.06
 9858.63 9886.08 9886.0810084.9010084.9010099.5010109.8110150.8010161.0510167.82
10181.5510191.8010202.0510232.8010253.2910273.8310294.3810314.9310335.4810356.03
10366.3010370.8310375.6110386.6110397.6110405.87
  387.39  386.67  383.91  382.18  381.15  377.27  376.35  373.92  373.01  371.09
  370.27  369.85  368.81  368.20  368.06  367.49  367.12  366.95  366.67  366.50
  366.24  366.14  365.79  365.57  365.62  365.52  365.19  364.97  364.97  365.22
  365.15  364.87  364.87  362.86  362.86  362.71  362.76  362.23  362.16  361.88
  361.47  361.33  361.09  360.04  359.14  358.70  359.13  359.87  360.78  361.96
  362.41  362.57  362.47  362.96  364.45  364.72
 -612.61 -613.33 -616.09 -617.82 -618.85 -622.73 -623.65 -626.08 -626.99 -628.91
 -629.73 -630.15 -631.19 -631.80 -631.94 -632.51 -632.88 -633.05 -633.33 -633.50
 -633.76 -633.86 -634.21 -634.43 -634.38 -634.48 -634.81 -635.03 -635.03 -634.78
 -634.85 -635.13  358.87  356.86 -637.14 -637.29 -637.24 -637.77 -637.84 -638.12
 -638.53 -638.67 -638.91 -639.96 -640.86 -641.30 -640.87 -640.13 -639.22 -638.04
 -637.59 -637.43 -637.53 -637.04 -635.55 -635.28
 9340.66 9349.79 9371.01 9386.48 9405.77 9472.07 9484.30 9520.95 9533.13 9562.54
 9581.86 9594.04 9615.07 9632.58 9642.77 9654.95 9667.60 9679.31 9685.12 9691.49
 9703.68 9715.86 9728.04 9740.22 9752.46 9772.17 9801.66 9813.95 9850.85 9858.06
 9858.63 9875.47 9875.4710074.2810074.2810099.5010109.8110150.8010161.0510167.82
10181.5510191.8010202.0510232.8010253.2910273.8310294.3810314.9310335.4810356.03
10366.3010370.8310375.6110386.6110397.6110405.87
  387.39  386.67  383.91  382.18  381.15  377.27  376.35  373.92  373.01  371.09
  370.27  369.85  368.81  368.20  368.06  367.49  367.12  366.95  366.67  366.50
  366.24  366.14  365.79  365.57  365.62  365.52  365.19  364.97  364.97  365.22
  365.15  364.98  364.98  362.97  362.97  362.71  362.76  362.23  362.16  361.88
  361.47  361.33  361.09  360.04  359.14  358.70  359.13  359.87  360.78  361.96
  362.41  362.57  362.47  362.96  364.45  364.72
 -612.61 -613.33 -616.09 -617.82 -618.85 -622.73 -623.65 -626.08 -626.99 -628.91
 -629.73 -630.15 -631.19 -631.80 -631.94 -632.51 -632.88 -633.05 -633.33 -633.50
 -633.76 -633.86 -634.21 -634.43 -634.38 -634.48 -634.81 -635.03 -635.03 -634.78
 -634.85 -635.02  358.98  356.97 -637.03 -637.29 -637.24 -637.77 -637.84 -638.12
 -638.53 -638.67 -638.91 -639.96 -640.86 -641.30 -640.87 -640.13 -639.22 -638.04
 -637.59 -637.43 -637.53 -637.04 -635.55 -635.28
Pier Skew, UpSta & Num, DnSta & Num=  ,9985.49, 2 ,9974.88, 2 , 0 , 0 , 0 ,,
    4.00    4.00
 -636.13  363.87
    4.00    4.00
 -636.03  363.97
BR Coef=-1 , 0 , 0 ,, 0 ,,,0.8,0,1,0,
WSPro=,,,, 1 ,,,, 0 ,,,, 0 ,,,,-1 ,-1 ,-1 , 0 , 0 , 0 , 0 , 0
BC Design=,, 0 ,, 0 ,,,,,,

Type RM Length L Ch R = 1 ,67196.36,614.181400,614.181400,614.181400
XS GIS Cut Line= 6
684292.654944693746652.028490205683970.618117601746484.211331055
683725.311453879746230.625031859683649.790620565746146.423642978
683543.887842804 745819.16669853 683205.80729568745769.925750569
#Sta/Elev= 30
9236.449399.03989299.236391.13189442.371386.59649500.266379.54919613.413385.2108
 9638.57385.40889673.174379.69169735.308382.48419742.603379.35119756.808361.3833
9763.186357.38739862.472351.37369897.816 334.1269933.391328.85329969.224331.1159
10029.13326.883610044.11332.093810068.41345.700310172.78352.515610274.18352.1793
10312.49355.905110360.35 364.87910518.52371.500610528.77374.606910549.25391.2319
10589.52391.791910639.75403.442510679.93404.242610700.02 410.55610759.49414.7151
#Mann= 3 , 0 , 0
9236.449  0.0653       09236.449  0.0653       010759.49  0.0653       0
#XS Ineff= 2 , 0
       09836.712        10097.61       0
Bank Sta=9236.449,10759.49
Exp/Cntr=0.3,0.1