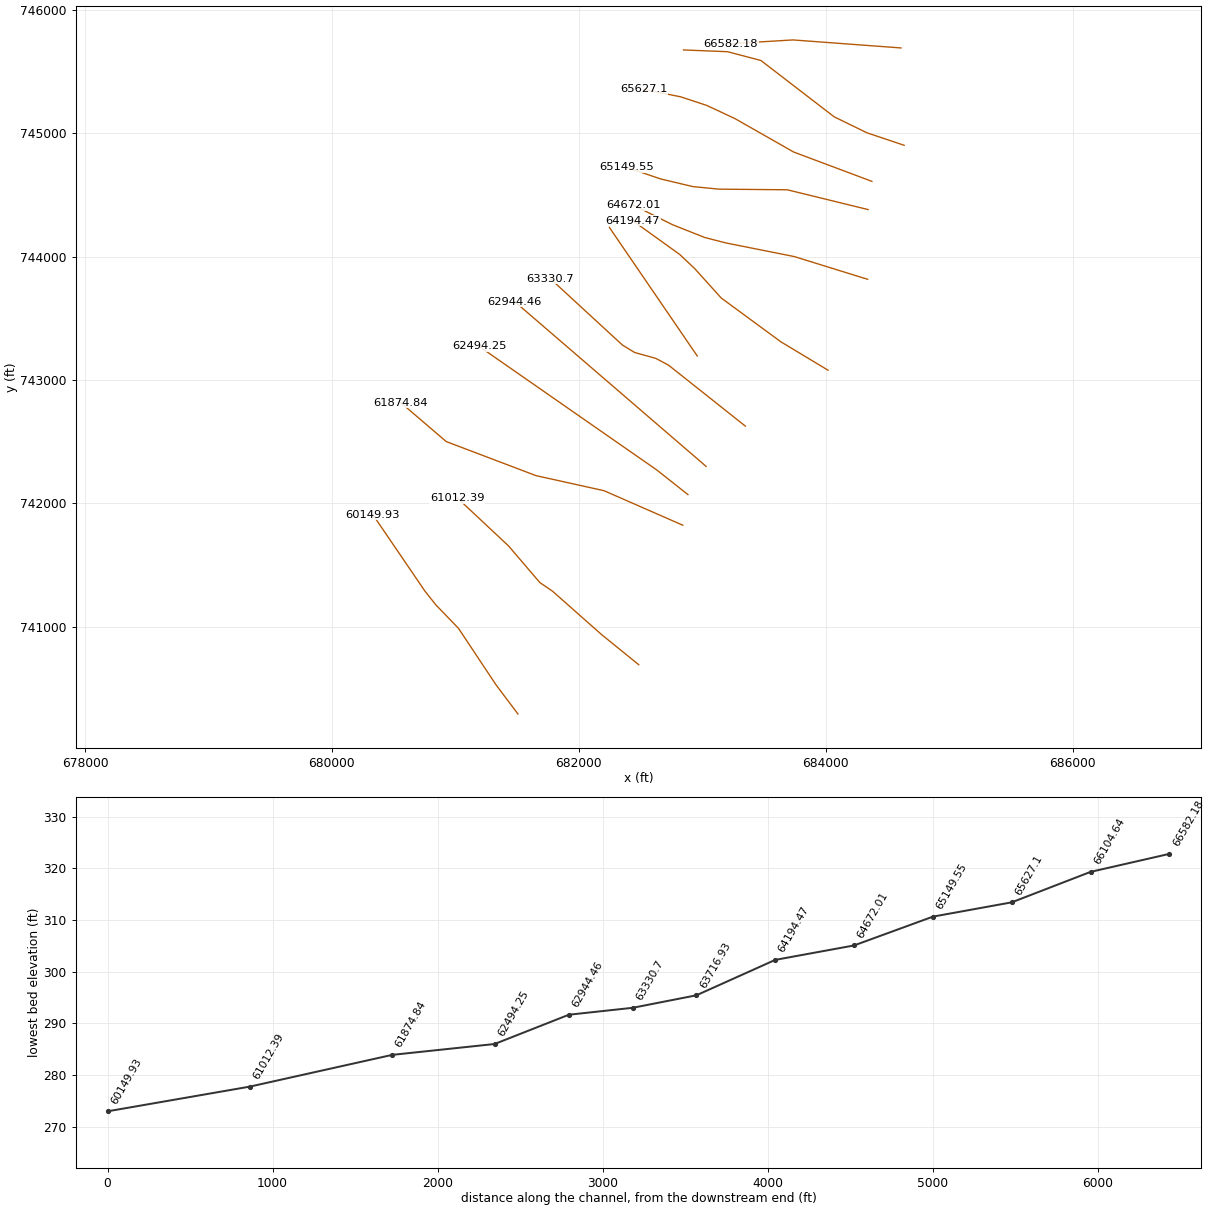
HEC-RAS study 3955_ras.prj: 3955

--- 3955_ras.g01 (geometry) --- (continued)

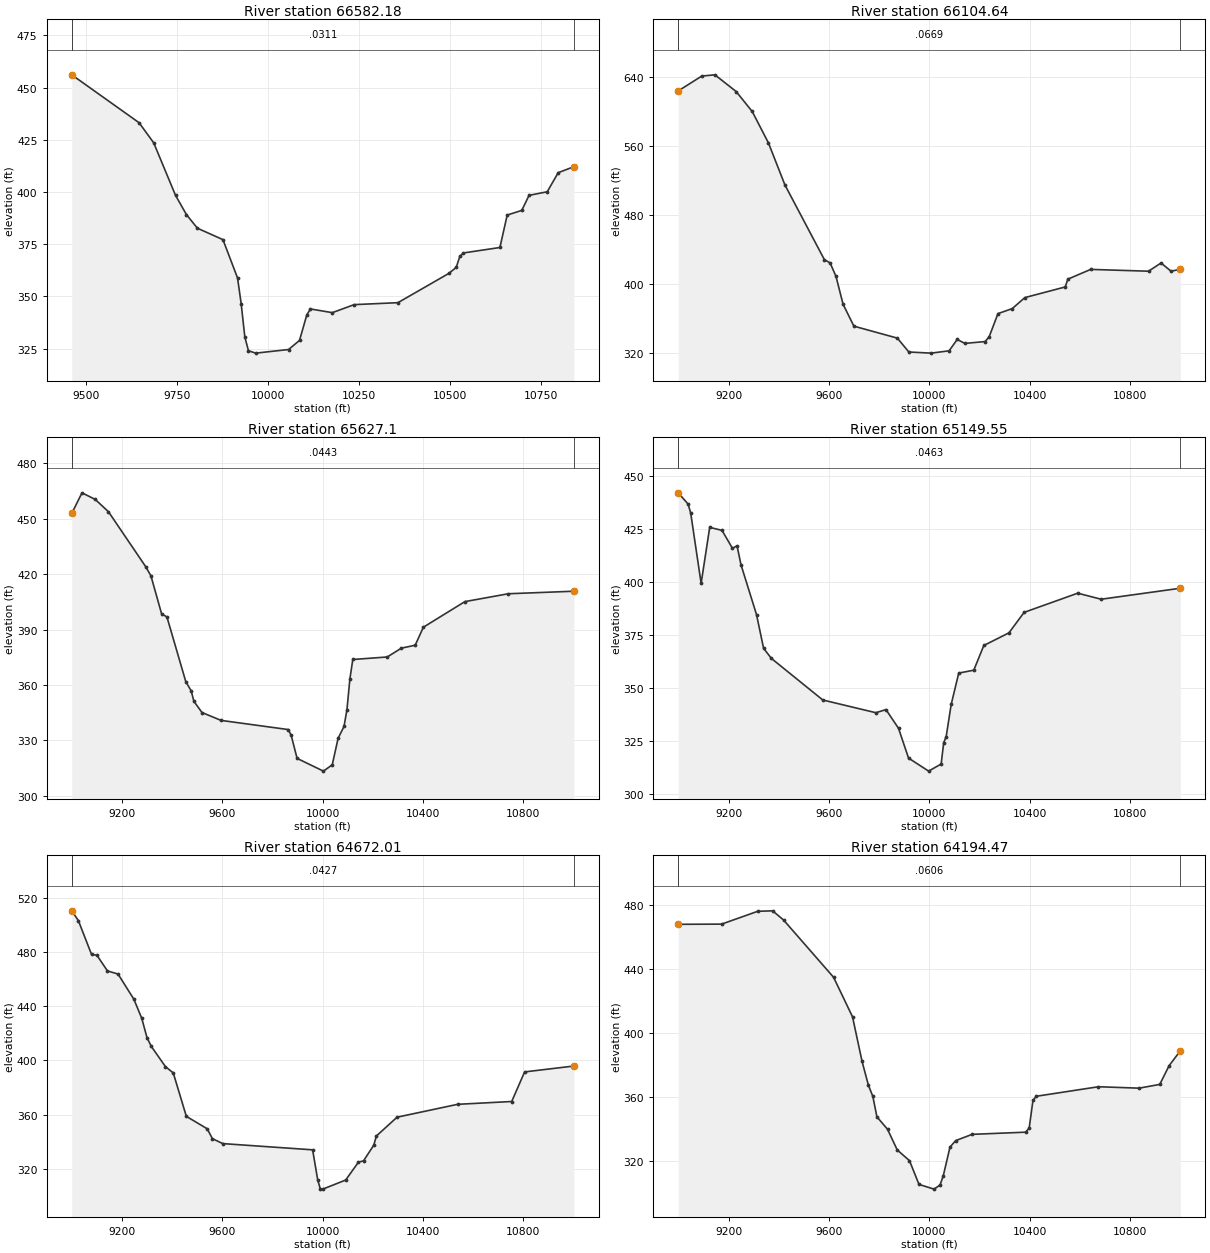
Type RM Length L Ch R = 1 ,66582.18,477.540300,477.540300,477.540300
XS GIS Cut Line= 3
684609.701375127 745689.57723482683734.523610294745754.494266838
683231.993443131745724.342456788
#Sta/Elev= 30
9460.618456.13329645.827433.18129685.937423.56689746.102398.36319776.184 389.125
9806.267382.63979876.459377.16979916.569358.82519926.596346.47619936.624330.5265
9946.651323.92599966.706322.800210056.95324.531110087.04328.891510107.09341.0966
10117.12343.960710177.28342.190410237.45346.036510357.76346.970610498.01361.0177
10518.05363.869810528.06 369.15310538.08 370.80110638.26373.4066 10658.3388.9537
10698.37391.173410718.41398.3879 10768.5400.117910798.55409.243910841.63412.1137
#Mann= 3 , 0 , 0
9460.618  0.0311       09460.618  0.0311       010841.63  0.0311       0
#XS Ineff= 2 , 0
       0                10572.68       0
Bank Sta=9460.618,10841.63
Exp/Cntr=0.3,0.1

Type RM Length L Ch R = 1 ,66104.64,477.540200,477.540200,477.540200
XS GIS Cut Line= 6
 684634.79224134744901.230588427684334.564016461745001.884589588
684069.151403604745131.145224735683474.489557721745588.174228122
683204.763217744745659.095173756682848.214157507745673.364971123
#Sta/Elev= 30
8999.061624.3134 9092.91641.58569145.253643.01099229.997623.59059294.024600.3589
9358.616563.89819424.417514.94739581.609428.14129604.613 424.1859628.035408.6303
9656.304376.15659699.518350.66789872.751336.76189918.656320.605410007.78319.3136
10079.09322.016510111.46 335.21710141.83330.633210222.96332.772610239.11338.6014
 10273.9365.263210330.85371.106810381.13383.898910542.19396.298710552.37405.3287
10643.59416.701910874.16 414.59710924.16424.153610964.16414.556411000.94416.9203
#Mann= 3 , 0 , 0
8999.061  0.0669       08999.061  0.0669       011000.94  0.0669       0
#XS Ineff= 2 , 0
       0                10521.44       0
Bank Sta=8999.061,11000.94
Exp/Cntr=0.3,0.1

Type RM Length L Ch R = 1 , 65627.1,477.540300,477.540300,477.540300
XS GIS Cut Line= 6
684373.693950302744608.951653507683740.130075873744846.485760973
683265.554896781745116.869230898 683036.11842259745224.083898731
682826.882107805745293.155561326 682528.70468656745354.339389954
#Sta/Elev= 30
8999.052452.92359039.818464.04659092.496 460.4879145.342453.81929293.385424.1705
9314.649419.13029357.177 398.5769378.502396.86329453.752361.81379475.252356.8562
9486.001351.19419518.251 345.139  9594.3340.87429862.372335.91019874.055332.7446
9897.421320.321410002.47313.417410037.64316.836810061.09331.231610084.55337.5887
10096.27346.6944   10108363.352810119.63373.837810257.03375.199410313.13379.9651
10368.41381.571910401.04391.316210566.39405.162410739.61409.420411000.95410.7915
#Mann= 3 , 0 , 0
8999.052  0.0443       08999.052  0.0443       011000.95  0.0443       0
#XS Ineff= 2 , 0
       0                               0
Bank Sta=8999.052,11000.95
Exp/Cntr=0.3,0.1

Type RM Length L Ch R = 1 ,65149.55,477.540300,477.540300,477.540300
XS GIS Cut Line= 6
684342.748904115744380.497641956683688.323427924744540.763698703
683136.167067774744545.829667933682923.566319283744566.573443445
682662.927199527744628.500163172682385.648538772744722.552251771
#Sta/Elev= 30
8999.055441.93059038.318436.63189048.719432.41549090.324399.20759124.496425.6256
9173.533424.23099215.138415.76239233.567 416.9529249.255408.00459311.174384.4865
9339.394368.58929370.406363.82619575.429 344.2059787.266338.19829827.296339.6809
9877.321330.84679917.325316.80469997.374310.647810047.41314.006810057.42324.0117
10067.43326.971410087.44342.158210117.47356.895910177.48358.269110217.48369.9182
10317.66375.876810378.08385.535610591.89394.586610685.21391.732611000.92396.9216
#Mann= 3 , 0 , 0
8999.055  0.0463       08999.055  0.0463       011000.92  0.0463       0
#XS Ineff= 2 , 0
       0                               0
Bank Sta=8999.055,11000.92
Exp/Cntr=0.3,0.1

Type RM Length L Ch R = 1 ,64672.01,477.540200,477.540200,477.540200
XS GIS Cut Line= 6
684339.787166924743815.569705701683744.728510581743999.880862771
683190.728048043 744110.28882881683019.710401775744154.335900594
682759.648477758744257.546675209682440.134454312744417.013833049
#Sta/Elev= 30
8999.021510.40329025.176503.25579077.937478.20079099.041477.6838 9141.25466.0843
9183.457 463.7589246.463445.23239277.966 431.1799298.968 416.8189316.345410.3213
9372.432395.4744 9403.71390.80769455.841 358.7689539.041349.58779559.744342.3262
9601.149338.65679959.337334.06669979.575312.00949989.693305.3782 9999.81305.0704
10091.14311.774310142.09324.977710162.48325.947310203.35337.556410213.61344.2662
   10296358.143310537.52367.642310753.15369.719310804.67391.548711000.94395.8977
#Mann= 3 , 0 , 0
8999.021  0.0427       08999.021  0.0427       011000.94  0.0427       0
#XS Ineff= 2 , 0
       0                               0
Bank Sta=8999.021,11000.94
Exp/Cntr=0.3,0.1

Type RM Length L Ch R = 1 ,64194.47,477.540300,477.540300,477.540300
XS GIS Cut Line= 6
684018.677392815743079.402086176683637.390810972743308.734396536
683152.889486647743664.519551524682940.099058635743900.651197783
 682817.83416067 744016.38038856 682437.61545232744289.763496428
#Sta/Elev= 30
8999.067467.99599172.045468.11769316.093476.14069375.411476.43469418.955 470.706
9618.466434.84319693.956410.11459732.045382.16289757.439367.21839774.985360.3132
9791.214347.51169833.619339.7222 9872.36326.77969921.048320.08929959.014305.2298
10018.99302.275410043.02304.858710055.96310.728110082.58 328.57110105.01 332.624
10170.93336.559410384.11337.912610398.26  340.4610413.45357.791910426.54360.3861
10674.45366.3444 10836.6365.459810919.03367.813710956.24379.5433 11000.9388.8278
#Mann= 3 , 0 , 0
8999.067  0.0606       08999.067  0.0606       0 11000.9  0.0606       0
#XS Ineff= 2 , 0
       0                               0
Bank Sta=8999.067,11000.9
Exp/Cntr=0.3,0.1

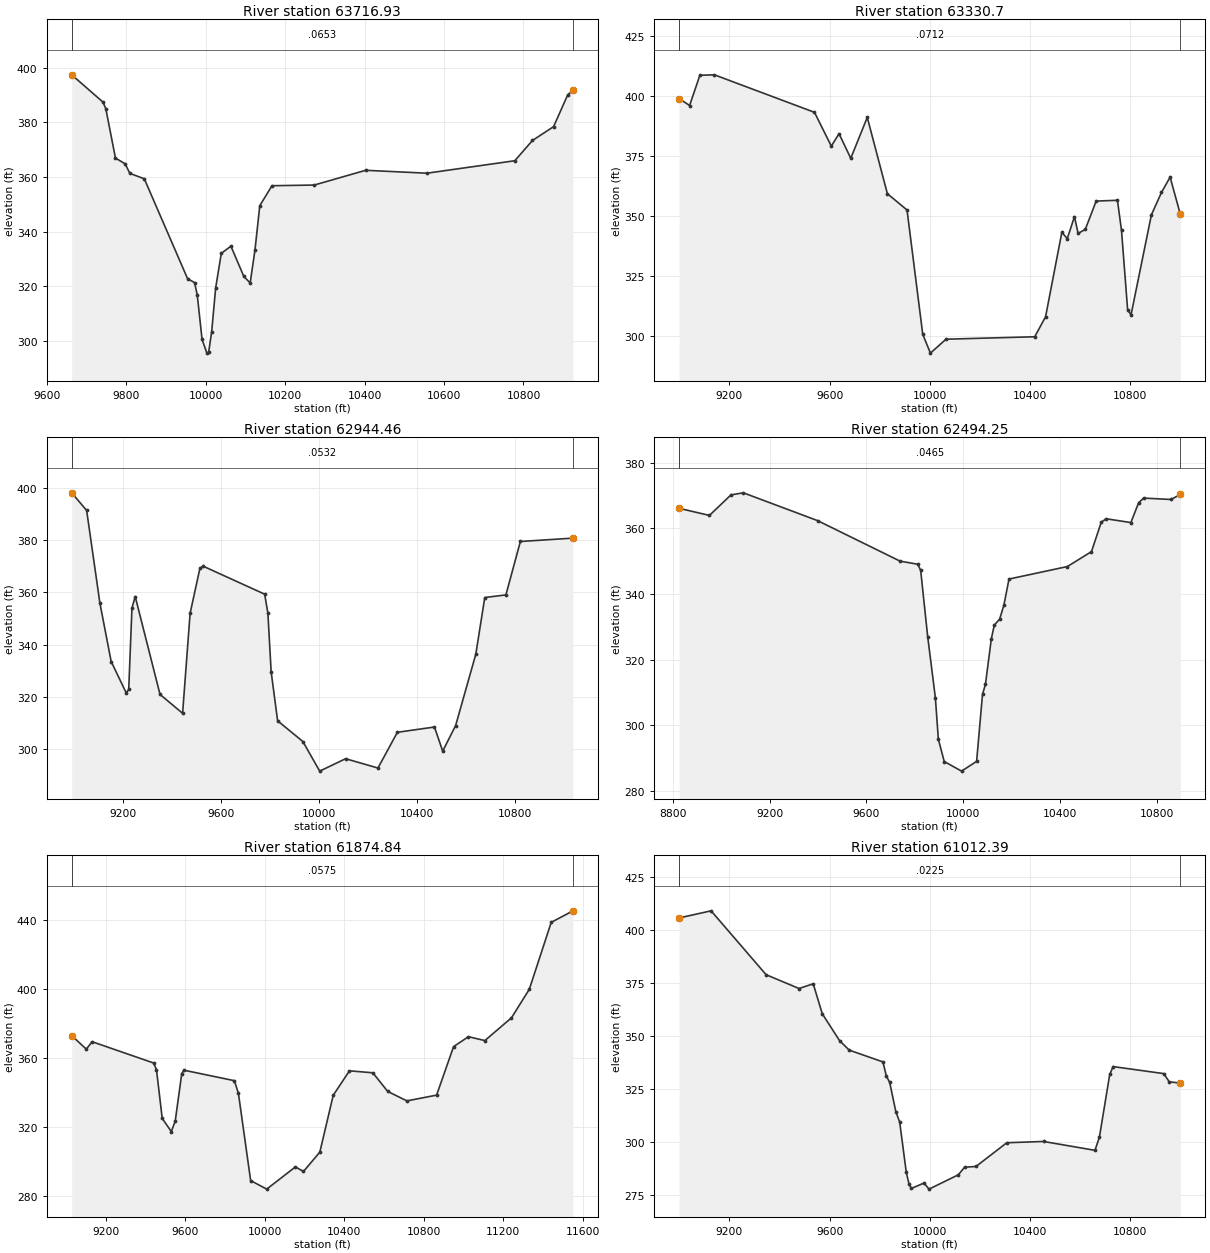
Type RM Length L Ch R = 1 ,63716.93,386.238400,386.238400,386.238400
XS GIS Cut Line= 2
682959.457080513743194.145293996 682247.44223699744235.885132104
#Sta/Elev= 30
9662.773397.46879741.559387.45029748.596385.03279772.822 366.9579797.047364.8461
9809.159361.33259845.497359.33879954.511322.68279971.942321.28689978.736316.7937
9990.849300.458810002.96295.418110007.39295.665810015.07303.310310025.11319.3329
 10039.3332.008910063.52334.638610095.99323.543610111.97321.146910124.09333.2507
 10136.2349.494910166.88356.806110273.21357.049110402.68 362.46210556.76361.3941
10778.17365.967610822.59373.399710875.75378.4658 10911.2390.076810924.59391.8567
#Mann= 3 , 0 , 0
9662.773  0.0653       09662.773  0.0653       010924.59  0.0653       0
#XS Ineff= 2 , 0
       0                               0
Bank Sta=9662.773,10924.59
Exp/Cntr=0.3,0.1

Type RM Length L Ch R = 1 , 63330.7,386.238400,386.238400,386.238400
XS GIS Cut Line= 6
683348.990678521742626.407791515682726.073645905743120.670178592
682622.448108629743175.621866785682453.391217331743222.260865452
682354.005899239743282.393991934681768.157021124743821.836252965
#Sta/Elev= 30
8999.125  399.039041.056396.1323 9082.11408.72239140.228408.91219539.799393.2929
9606.962379.21459637.874384.3876 9684.63374.1418 9750.55391.17249830.873359.4048
9909.363352.60469972.113300.851810002.75292.998210064.93298.796710419.36299.8152
10462.65308.152710527.64343.340810549.21340.690410578.07349.8517 10592.5342.8592
10621.35344.552510664.64356.328410749.61356.651510765.84344.088210790.43310.9435
10803.97308.969110885.22350.584110925.51359.926410959.97366.296511000.85 350.783
#Mann= 3 , 0 , 0
8999.125  0.0712       08999.125  0.0712       011000.85  0.0712       0
#XS Ineff= 2 , 0
       09813.873        10291.95       0
Bank Sta=8999.125,11000.85
Exp/Cntr=0.3,0.1

Type RM Length L Ch R = 1 ,62944.46,450.207200,450.207200,450.207200
XS GIS Cut Line= 2
683031.081436127 742300.09222354681482.470325023743633.425556898
#Sta/Elev= 30
8992.237398.12499053.045  391.399107.043355.95279153.022333.59599214.328321.5937
9224.591322.90079237.786354.00559250.982358.45479352.266320.98649444.224313.7875
9474.877352.02969514.899369.27879528.094370.05929778.815359.35029792.011352.0254
9805.207329.69949831.598310.91179934.669302.972310003.14291.658210108.71296.4074
10240.67292.846810319.84306.513910471.09308.529310504.59299.299910557.37   309.1
10639.68336.424610676.13358.068510762.29359.082410821.29 379.51111035.76 380.794
#Mann= 3 , 0 , 0
8992.237  0.0532       08992.237  0.0532       011035.76  0.0532       0
#XS Ineff= 2 , 0
       0 9708.24        10280.33       0
Bank Sta=8992.237,11035.76
Exp/Cntr=0.3,0.1

Type RM Length L Ch R = 1 ,62494.25,619.405700,619.405700,619.405700
XS GIS Cut Line= 3
 682883.48898977742071.897026017682630.673591435742271.841200188
681193.173591465743271.841200188
#Sta/Elev= 30
8824.949366.13648950.516363.9769 9039.52370.2386 9090.76370.86519397.818362.3871
9738.905350.03459811.995349.08799824.177347.25069853.251326.99519885.085308.3266
9897.267295.7603 9921.63288.9213 9993.34 285.98610055.63288.958110079.99309.3857
10092.17312.480610116.54326.337810128.72330.516510150.94332.350610168.45336.6102
10189.63344.569310431.12348.383410530.71352.922410571.21361.900210591.62 362.955
10693.79361.796810725.62367.809510746.32369.255910859.62368.838910898.39370.3628
#Mann= 3 , 0 , 0
8824.949  0.0465       08824.949  0.0465       010898.39  0.0465       0
#XS Ineff= 2 , 0
       0                               0
Bank Sta=8824.949,10898.39
Exp/Cntr=0.3,0.1

Type RM Length L Ch R = 1 ,61874.84,862.459300,862.459300,862.459300
XS GIS Cut Line= 5
682842.138183326741823.792187303682204.154312372742103.402402341
681652.810226351  742225.4857357680926.217484385 742501.15777868
680557.998398423742816.211542115
#Sta/Elev= 30
9028.519372.99479101.822365.16069131.176369.46939440.288357.12629455.033353.2841
9483.961324.97359529.769317.2892 9549.47 323.4189582.225350.86519593.143352.9375
9847.126346.85139867.611339.46859929.064288.858710010.01283.888310154.39296.7909
10195.03294.1388 10277.3 305.367 10344.8338.380710426.48352.575910544.14351.4288
   10619340.621410715.26335.1134   10865338.459310950.57366.622311025.44372.3824
   11108370.138311242.02383.352111331.73399.914311441.99438.762611551.52445.4576
#Mann= 3 , 0 , 0
9028.519  0.0575       09028.519  0.0575       011551.52  0.0575       0
#XS Ineff= 2 , 0
       09816.419                       0
Bank Sta=9028.519,11551.52
Exp/Cntr=0.3,0.1

Type RM Length L Ch R = 1 ,61012.39,862.459200,862.459200,862.459200
XS GIS Cut Line= 6
682485.255860646740693.938346018 682185.43805876740936.855391943
681786.723023274741289.549558633681684.333028546741359.245903332
681430.393559365741656.293113294681015.748158777742044.711746744
#Sta/Elev= 30
8999.066405.69739126.867409.05279346.581378.91089478.254372.39479534.655374.6378
9570.962360.45969640.111347.77679678.553343.32249813.213337.76219826.679331.1219
9840.145328.08159864.489314.34449879.932309.42389906.371285.65129917.313280.1631
 9926.28278.05239977.309 280.6149997.161277.7427 10114.2284.505310139.35288.0877
10184.74288.431510307.68299.625410454.35300.228710659.88296.050110677.49302.1859
10718.87331.846310732.35335.560110934.51332.248610956.57 328.37711000.89327.7587
#Mann= 3 , 0 , 0
8999.066  0.0225       08999.066  0.0225       011000.89  0.0225       0
#XS Ineff= 2 , 0
       0                               0
Bank Sta=8999.066,11000.89
Exp/Cntr=0.3,0.1

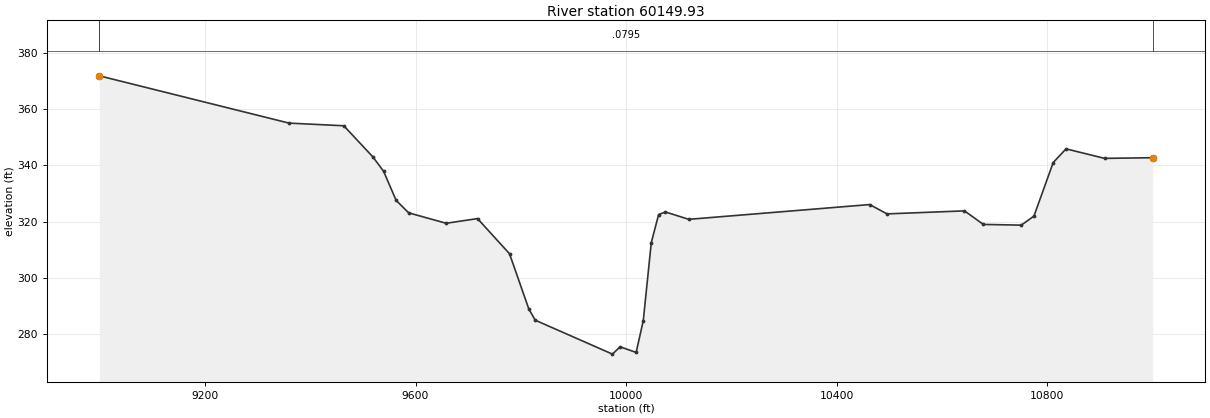
Type RM Length L Ch R = 1 ,60149.93,393.003400,393.003400,393.003400
XS GIS Cut Line= 6
681506.758846343740294.890708354681330.727782996740528.804861053
681024.520909585740989.517817765680843.715827059741176.583221471
680755.501083081741287.079730656680331.171881644 741910.03911275
#Sta/Elev= 30
8999.078371.77789359.642354.98519463.633354.04339518.991342.97399539.305337.8716
9563.102327.5593  9586.9323.12579658.292 319.4249717.786321.08239778.573308.5913
  9815.2289.0271 9827.41285.01199974.195272.95729988.789275.557510019.22273.5593
10032.76284.815710047.99312.575810061.98322.522910074.96323.432710119.24320.8222
10463.04326.065810496.01322.753110643.11323.828310679.12319.009510751.15318.7616
10775.18321.965610811.79340.992510836.19345.844810909.39342.469211000.95342.6956
#Mann= 3 , 0 , 0
8999.078  0.0795       08999.078  0.0795       011000.95  0.0795       0
#XS Ineff= 2 , 0
       0                               0
Bank Sta=8999.078,11000.95
Exp/Cntr=0.3,0.1