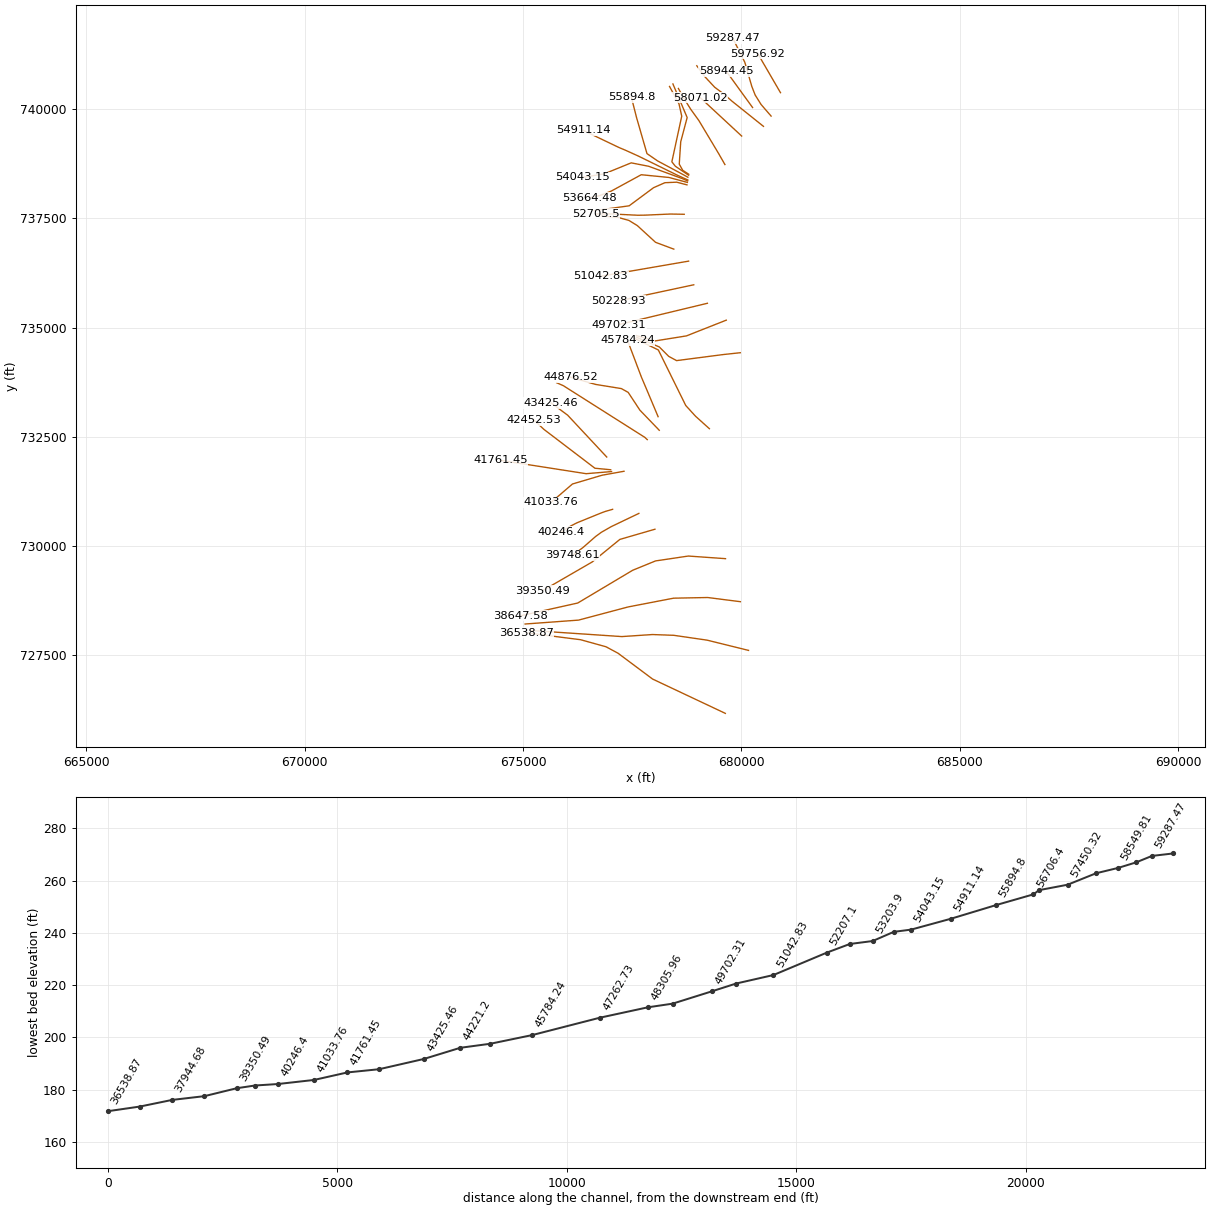
HEC-RAS study 3955_ras.prj: 3955

--- 3955_ras.g01 (geometry) --- (continued)

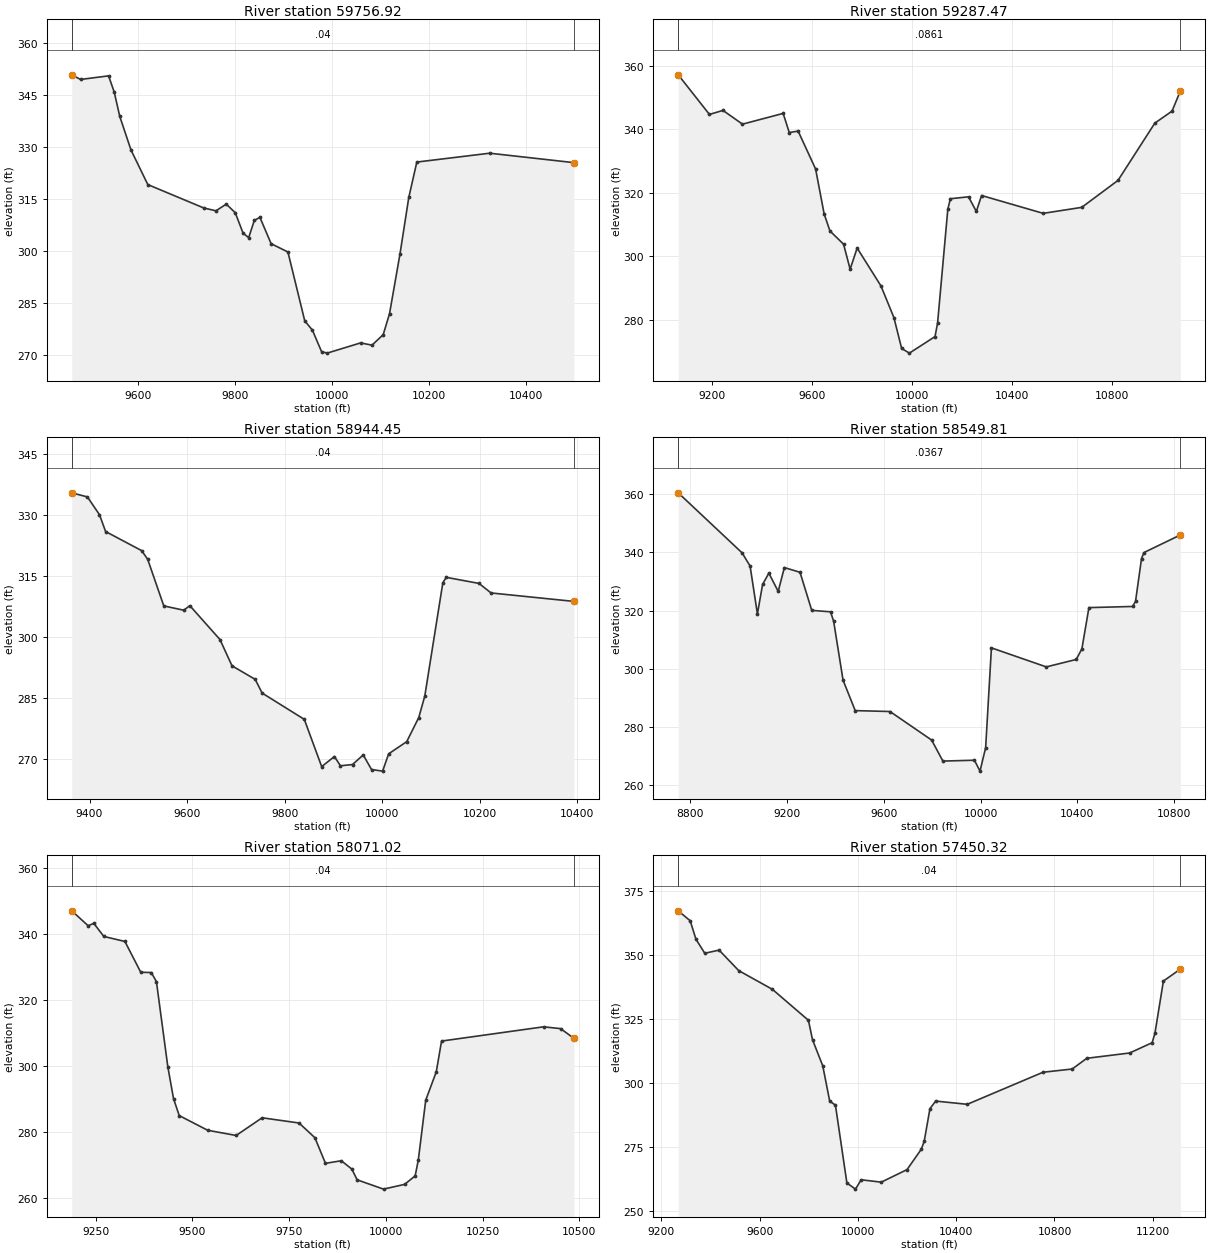
Type RM Length L Ch R = 1 ,59756.92,469.455900,469.455900,469.455900
XS GIS Cut Line= 2
680894.613032997740379.329455316680373.779699683741275.162788659
#Sta/Elev= 30
9463.329 350.7329481.455349.39439539.292350.43329550.859345.80349562.426338.7121
9585.561329.04569620.263319.05949735.935312.29929760.995311.48949782.205313.4196
9800.786310.92619816.906 305.0329828.474303.74759840.041308.69729851.608309.6153
9874.743302.00649909.445   299.69944.147279.74019959.952277.04919978.848270.8611
9990.416270.417810059.43273.368510082.95 272.71710106.09275.748410119.12281.7807
10140.79299.071610158.91 315.35310175.49325.556710325.87328.111310499.56325.3907
#Mann= 3 , 0 , 0
9463.329    0.04       09463.329    0.04       010499.56    0.04       0
#XS Ineff= 2 , 0
       0                               0
Bank Sta=9463.329,10499.56
Exp/Cntr=0.3,0.1

Type RM Length L Ch R = 1 ,59287.47,343.015300,343.015300,343.015300
XS GIS Cut Line= 6
680679.862285725739843.183779781680450.313005835740108.945158869
680315.522422642740324.337418154680237.494717747740523.425391644
680077.630125344741076.201885134679803.808224708741623.808464184
#Sta/Elev= 30
9063.558357.11099188.425344.63269242.557345.9037 9320.68341.57149483.352 344.961
9507.758338.93849543.294339.38759613.273327.42659647.351313.31079670.565307.9396
9725.115303.7548  9751.3295.89039779.419302.54789874.596 290.6259926.433280.6611
9957.456270.91839988.479269.448310091.06274.665710101.27 278.94410142.24314.8134
10152.53 318.08310225.05318.6844 10256.3314.074510277.27319.0992 10523.9313.4764
   10678315.364310823.09323.850110970.55341.901611039.39345.681111072.44352.0177
#Mann= 3 , 0 , 0
9063.558  0.0861       09063.558  0.0861       011072.44  0.0861       0
#XS Ineff= 2 , 0
       0                               0
Bank Sta=9063.558,11072.44
Exp/Cntr=0.3,0.1

Type RM Length L Ch R = 1 ,58944.45,394.641300,394.641300,394.641300
XS GIS Cut Line= 2
680255.724144101 740039.05167754679651.557477474740872.385010883
#Sta/Elev= 30
9363.577335.44759395.628334.43889420.331330.07629432.958325.92379506.792321.2329
9519.144319.10859552.215307.62889593.254306.57119605.605307.69269667.363299.3612
9692.067292.89219739.619289.55899753.825286.18759840.286279.72169875.913268.0994
9902.044270.57539914.396 268.2989939.099268.60619961.096270.96539978.133267.3715
10000.86 266.98510013.21271.244710050.26274.235910074.97280.172410087.32285.4635
10124.37313.371710131.46314.655410198.48313.159310223.19310.815810392.88308.7385
#Mann= 3 , 0 , 0
9363.577    0.04       09363.577    0.04       010392.88    0.04       0
#XS Ineff= 2 , 0
       0                               0
Bank Sta=9363.577,10392.88
Exp/Cntr=0.3,0.1

Type RM Length L Ch R = 1 ,58549.81,478.786900,478.786900,478.786900
XS GIS Cut Line= 6
680504.898750398739607.986896244679787.974153042740181.777479753
679588.112990916 740355.16056703679389.414362788740502.554509878
679165.079431981740742.760124475678978.000176728740995.667236164
#Sta/Elev= 30
8750.844360.4558 9014.78339.82639047.742  335.319077.993318.8667  9099.4328.9689
9125.228332.86319163.881326.58679189.333334.7865    9254333.15539302.503320.0818
9380.229319.57439392.955316.33929431.844296.10679482.039285.64339625.857285.3293
9797.831275.52539844.381268.30379974.632268.59949997.725264.852210021.03272.9261
10044.94307.193710271.58300.657110395.07303.206910418.61306.821410447.76321.0232
10627.85321.416810640.25323.130910665.06337.857610674.87339.932910825.35345.9734
#Mann= 3 , 0 , 0
8750.844  0.0367       08750.844  0.0367       010825.35  0.0367       0
#XS Ineff= 2 , 0
       0                               0
Bank Sta=8750.844,10825.35
Exp/Cntr=0.3,0.1

Type RM Length L Ch R = 1 ,58071.02,620.705900,620.705900,620.705900
XS GIS Cut Line= 2
680005.724144131739386.273899764679054.335255235740268.218344226
#Sta/Elev= 30
9188.311346.97239230.565342.47329245.275343.17549271.113339.22829325.656337.7057
9366.563328.39489393.835328.30679407.079325.54319436.498299.81439451.207290.2039
9465.917285.05639539.464280.61389613.011279.03689680.186284.38849775.636282.8071
9816.544278.35649843.815270.61039884.723271.39819911.994268.8739 9925.63265.6284
9993.809262.812610048.35264.252710075.62266.822310083.71271.611610102.89289.7063
10130.17298.3008 10143.8307.586910407.32311.893910451.45311.3492 10485.6308.4239
#Mann= 3 , 0 , 0
9188.311    0.04       09188.311    0.04       0 10485.6    0.04       0
#XS Ineff= 2 , 0
       0                               0
Bank Sta=9188.311,10485.6
Exp/Cntr=0.3,0.1

Type RM Length L Ch R = 1 ,57450.32,621.706000,621.706000,621.706000
XS GIS Cut Line= 6
679621.897575289 738733.71101363679480.796814054738980.637345746
679025.691499978 739740.53796193 678835.63791278740004.499280497
678672.194289178740268.415173322678556.880759656   740475.270457
#Sta/Elev= 30
9268.848367.29329317.423363.41379340.952356.18799376.861 350.6889435.069351.9278
 9515.11343.89739652.175336.57539798.674324.47349815.362316.84729857.063306.6541
  9885.3292.84529908.612291.28099955.237260.81979990.206258.421410013.52 262.083
10095.11261.144710200.02266.0585 10258.3274.063710269.96 277.16410293.27289.8905
10316.58292.869610445.19291.603110753.41304.146210872.25305.410910931.56309.6065
11105.85311.671911197.54315.7003   11209319.419711243.38339.815711312.21344.4873
#Mann= 3 , 0 , 0
9268.848    0.04       09268.848    0.04       011312.21    0.04       0
#XS Ineff= 2 , 0
       0                10883.49       0
Bank Sta=9268.848,11312.21
Exp/Cntr=0.3,0.1

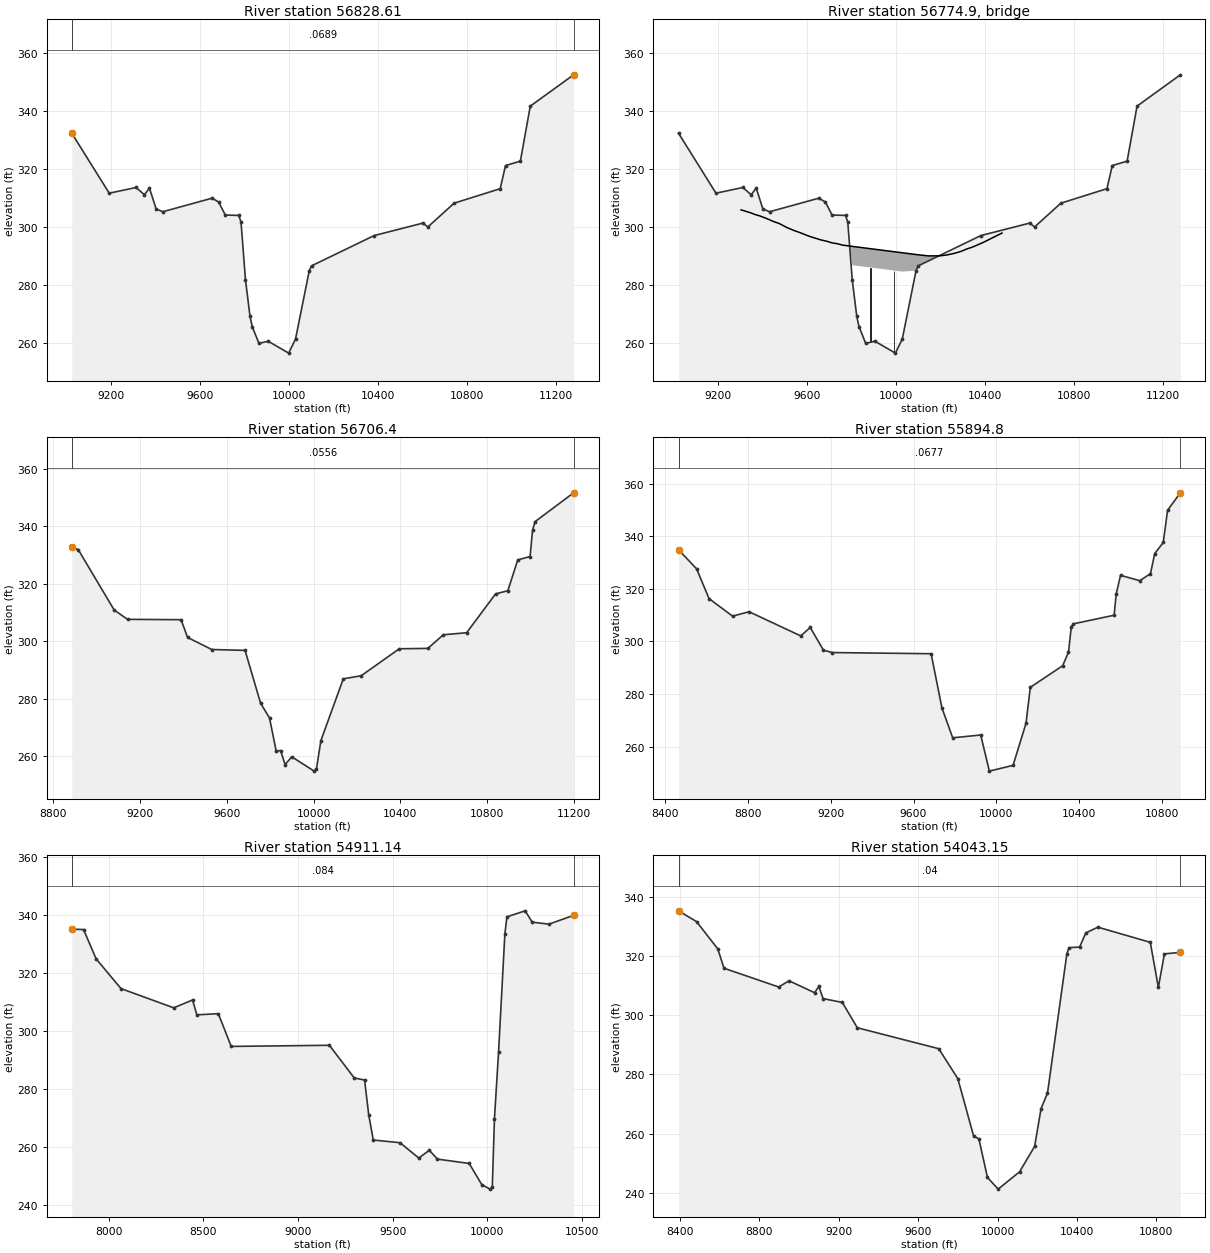
Type RM Length L Ch R = 1 ,56828.61,122.208800,122.208800,122.208800
XS GIS Cut Line= 6
678793.738727182738511.486054286678657.110064954738600.627925366
678576.554509461738742.294592053678609.887842774739253.405703157
678757.432989746739810.185323045678431.205861032740579.754538581
#Sta/Elev= 30
9024.465332.37969192.631311.64169313.254313.6082 9350.57311.10519373.284313.3796
9403.295306.19459433.307305.22579654.404309.91279683.605308.6135 9713.82 304.087
 9774.25303.95259784.322301.69989804.466281.66329824.609269.15289834.681265.5418
9864.927 259.7029906.002260.48129998.419256.350610029.23261.251110090.84284.8666
10101.11286.524210381.89296.987810601.01301.296710623.19299.969810741.01 308.179
10948.05313.197610971.87321.193711038.59322.721411083.07341.726711277.41352.5549
#Mann= 3 , 0 , 0
9024.465  0.0689       09024.465  0.0689       011277.41  0.0689       0
#XS Ineff= 2 , 0
       0                10623.84       0
Bank Sta=9024.465,11277.41
Exp/Cntr=0.3,0.1

Type RM Length L Ch R = 3 , 56774.9,,,
BEGIN DESCRIPTION:
END DESCRIPTION:
Bridge Culvert--1,0,-1,-1, 0
Deck Dist Width WeirC Skew NumUp NumDn MinLoCord MaxHiCord MaxSubmerge Is_Ogee
34.201550,53.805700,2.6,0, 29, 29, , , 0.95, 0, 0,0,,
 9305.08 9348.04 9368.34 9388.65 9419.11 9449.58 9477.14 9510.12 9540.24 9570.35
 9610.51 9661.83 9692.78 9713.42 9738.77 9759.42 9783.92 9783.9210095.2710095.27
10146.2010198.0910229.2310260.3710291.5110321.9710342.1510392.6210476.92
  305.88  304.86  304.26  303.81  302.91  301.89  301.13  299.80  298.82  297.99
  296.76  295.53  294.97  294.46  294.16  293.71  293.46  293.46  290.39  290.39
  289.96  289.99  290.28  290.80  291.48  292.45  292.94  294.62  297.86
 -694.12 -695.14 -695.74 -696.19 -697.09 -698.11 -698.87 -700.20 -701.18 -702.01
 -703.24 -704.47 -705.03 -705.54 -705.84 -706.29 -706.54  286.96  283.89 -709.61
 -710.04 -710.01 -709.72 -709.20 -708.52 -707.55 -707.06 -705.38 -702.14
 9305.08 9348.04 9368.34 9388.65 9419.11 9449.58 9477.14 9510.12 9540.24 9570.35
 9610.51 9661.83 9692.78 9713.42 9738.77 9759.42 9786.20 9786.2010097.5510097.55
10146.2010198.0910229.2310260.3710291.5110321.9710342.1510392.6210476.92
  305.88  304.86  304.26  303.81  302.91  301.89  301.13  299.80  298.82  297.99
  296.76  295.53  294.97  294.46  294.16  293.71  293.44  293.44  290.37  290.37
  289.96  289.99  290.28  290.80  291.48  292.45  292.94  294.62  297.86
 -694.12 -695.14 -695.74 -696.19 -697.09 -698.11 -698.87 -700.20 -701.18 -702.01
 -703.24 -704.47 -705.03 -705.54 -705.84 -706.29 -706.56  286.94  283.87 -709.63
 -710.04 -710.01 -709.72 -709.20 -708.52 -707.55 -707.06 -705.38 -702.14
Pier Skew, UpSta & Num, DnSta & Num=  ,9887.03, 2 ,9889.31, 2 , 0 , 0 , 0 ,,
    4.00    4.00
 -707.55  292.45
    4.00    4.00
 -707.58  292.42
Pier Skew, UpSta & Num, DnSta & Num=  ,9992.15, 2 ,9994.43, 2 , 0 , 0 , 0 ,,
    4.00    4.00
 -708.59  291.41
    4.00    4.00
 -708.61  291.39
BR Coef=-1 , 0 , 0 ,, 0 ,,,0.8,0,1,0,
WSPro=,,,, 1 ,,,, 0 ,,,, 0 ,,,,-1 ,-1 ,-1 , 0 , 0 , 0 , 0 , 0
BC Design=,, 0 ,, 0 ,,,,,,

Type RM Length L Ch R = 1 , 56706.4,811.606400,811.606400,811.606400
XS GIS Cut Line= 6
678790.064620405738489.686353967678487.144787252738694.829314262
678406.936453909738795.870980933678633.325342804739842.120980933
678570.825342745740123.370980933678354.048942387740521.066031292
#Sta/Elev= 30
8884.723  332.648914.414331.87899080.397310.82569142.183307.58139388.896307.4587
9418.942301.28869530.257 297.0829684.018296.77659755.773278.35649796.775273.2488
9827.528261.77179848.029261.89619868.575257.01599899.559259.721410002.84254.7348
10013.17 255.46510033.82265.3699 10137.1286.868510219.72287.9459 10395.3297.3333
10527.21297.468310598.38302.209210705.97  302.9210839.19316.428210896.13317.5566
10941.69328.274410998.64329.456811010.03338.627711021.41341.594811199.16351.6337
#Mann= 3 , 0 , 0
8884.723  0.0556       08884.723  0.0556       011199.16  0.0556       0
#XS Ineff= 2 , 0
       0                10510.33       0
Bank Sta=8884.723,11199.16
Exp/Cntr=0.3,0.1

Type RM Length L Ch R = 1 , 55894.8,983.654700,983.654700,983.654700
XS GIS Cut Line= 6
678774.176689029738442.981913283678590.781941056738543.719711483
678079.533960164738817.282227546677837.271340013738984.174254805
677600.392333537739802.483549684677479.798542947740274.638899446
#Sta/Elev= 30
8465.609334.82248552.884327.58488612.991316.24598726.774309.58058806.165311.2532
9055.681302.06819101.479305.27089165.067296.66749207.458295.73349685.068295.2874
9737.121274.72349789.173263.3137 9924.51264.37939966.153250.642610080.67252.8447
10143.13268.827210163.95282.509110320.11290.724610348.24295.875910361.75305.4891
10372.16306.660210568.51309.931910578.83318.090410599.47325.110610692.36323.0591
10743.97325.733110764.61333.395210805.89337.611110826.53349.850310888.09356.4765
#Mann= 3 , 0 , 0
8465.609  0.0677       08465.609  0.0677       010888.09  0.0677       0
#XS Ineff= 2 , 0
       0                10248.05       0
Bank Sta=8465.609,10888.09
Exp/Cntr=0.3,0.1

Type RM Length L Ch R = 1 ,54911.14,867.989700,867.989700,867.989700
XS GIS Cut Line= 6
678771.737609267738380.946087688678528.907365888738491.406461522
677646.268476993 738924.73979488677343.922876447739061.717681542
677193.699959099 739124.77421473 676377.72773689739515.399214745
#Sta/Elev= 30
7805.125335.09297867.457334.98627933.373324.89888065.205314.60288343.615307.9699
8443.108310.67898465.799305.54778579.253305.94378647.326294.65159165.887295.0442
9297.079283.77189351.743283.05479373.608271.0239 9397.58262.35879538.569261.4294
9638.077256.15039693.511258.8112 9736.62255.76559904.161254.27049970.682246.9602
10014.53245.410910026.12245.980910037.69269.771410059.38292.746810092.64333.4929
10103.72339.3696 10199.8341.436610236.77337.533410325.46336.839710455.48339.8669
#Mann= 3 , 0 , 0
7805.125   0.084       07805.125   0.084       010455.48   0.084       0
#XS Ineff= 2 , 0
       0                               0
Bank Sta=7805.125,10455.48
Exp/Cntr=0.3,0.1

Type RM Length L Ch R = 1 ,54043.15,378.673500,378.673500,378.673500
XS GIS Cut Line= 6
678767.921258569738358.302407011678653.907365888738408.767572656
677874.831436127738694.189445779677475.525880575738772.314445779
676859.206436157738520.578334659676365.251667529738439.899168909
#Sta/Elev= 30
8392.133335.26668482.814331.63288589.695322.43458621.425315.87088896.413309.5417
8949.295311.61069077.622307.60739099.137309.72819120.652305.60719217.471304.3183
9292.774 295.7669703.207288.68549799.409278.55959878.748 259.2099905.415258.2323
9948.623245.182410002.63241.242710110.65247.108710186.27255.685210218.67268.4587
10251.08273.6654 10348.3320.5633 10359.1322.826810413.11323.028110443.96327.7939
 10504.9329.7459   10769324.618910809.63309.3946 10840.1320.732610920.29321.2108
#Mann= 3 , 0 , 0
8392.133    0.04       08392.133    0.04       010920.29    0.04       0
#XS Ineff= 2 , 0
       0                               0
Bank Sta=8392.133,10920.29
Exp/Cntr=0.3,0.1

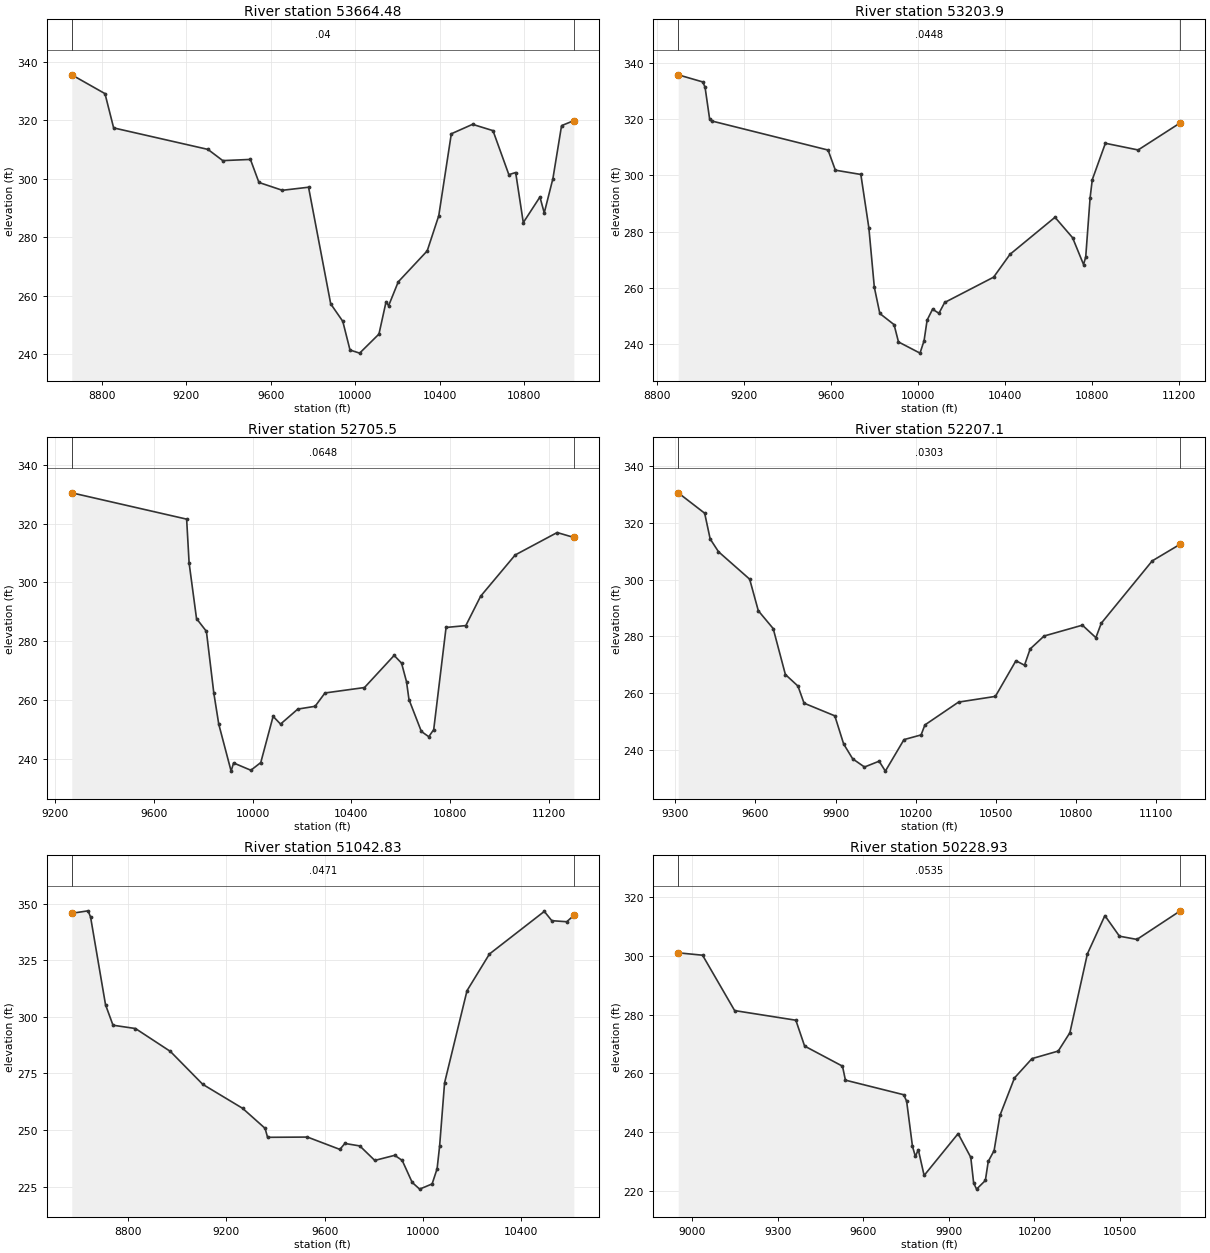
Type RM Length L Ch R = 1 ,53664.48,460.577900,460.577900,460.577900
XS GIS Cut Line= 6
678762.247784585738324.639794827678339.324032545738437.934239313
677705.990699172738500.434239313677017.654038996738124.837705031
676751.824032545738021.267572656676528.232006282737972.483857825
#Sta/Elev= 30
8659.088335.52858816.214 329.0988857.138317.38329303.237310.03219373.461306.1958
9504.208306.6084 9544.48298.73029655.229  296.059779.157297.10359883.996257.2199
9941.052251.26219975.285241.440810020.93240.380210112.22246.894610145.97257.9794
10157.86256.584610203.51 264.75210340.44275.331310395.09287.351410454.55315.3739
10555.04318.601210651.62316.445110726.75301.389710758.95302.1324   10795285.0011
10873.68293.761610894.15288.325110935.09300.044210976.03318.155511034.14319.8728
#Mann= 3 , 0 , 0
8659.088    0.04       08659.088    0.04       011034.14    0.04       0
#XS Ineff= 2 , 0
       0                               0
Bank Sta=8659.088,11034.14
Exp/Cntr=0.3,0.1

Type RM Length L Ch R = 1 , 53203.9,498.400700,498.400700,498.400700
XS GIS Cut Line= 6
678752.782875538738268.481334448678516.834479302  738329.9356969
678247.446337551738317.675308347677988.173270375 738203.53721033
677428.758507639737788.766173825676631.335982949 737676.78943415
#Sta/Elev= 30
8899.226335.77669012.229333.24329022.595331.35699043.326320.21729053.692319.3653
9588.259  309.04 9621.83 301.8889739.035300.36799775.932  281.389801.041260.2937
9826.369250.95519891.842246.99659912.136240.844910011.17 236.86910029.86 241.296
10043.88248.616110068.89252.471310098.15251.0305 10124.6254.8685 10349.7263.8679
10425.16271.994110631.97285.149810712.82277.893410763.28268.353510773.32271.0711
10793.41292.052810803.46298.524110863.73 311.45111014.25309.072611208.31318.7192
#Mann= 3 , 0 , 0
8899.226  0.0448       08899.226  0.0448       011208.31  0.0448       0
#XS Ineff= 2 , 0
       0                10506.78       0
Bank Sta=8899.226,11208.31
Exp/Cntr=0.3,0.1

Type RM Length L Ch R = 1 , 52705.5,498.400600,498.400600,498.400600
XS GIS Cut Line= 6
678690.243203796737594.614385933678372.234507591737600.201723635
677788.049274772737574.784328252677627.473305106 737572.63074927
677030.550070941737602.022315174676657.372447342737602.118819386
#Sta/Elev= 30
9267.415330.44959732.847321.49419742.858306.58139772.895287.64699812.944283.3054
9842.981262.30549863.006251.70989913.067235.7293 9923.08238.50879993.166236.0276
10033.21238.646110083.25254.380510113.28251.740810183.34256.845910253.37257.7877
10293.37262.329610453.45  264.1810573.68275.109810603.74272.484210623.78266.1523
 10633.8260.086210683.89249.240610713.95 247.44110733.99249.858210784.04284.6257
10864.09285.263710924.14295.264711064.15309.300711234.15316.933511301.79315.2664
#Mann= 3 , 0 , 0
9267.415  0.0648       09267.415  0.0648       011301.79  0.0648       0
#XS Ineff= 2 , 0
       0                10419.95       0
Bank Sta=9267.415,11301.79
Exp/Cntr=0.3,0.1

Type RM Length L Ch R = 1 , 52207.1,1164.264800,1164.264800,1164.264800
XS GIS Cut Line= 6
678451.875280123736796.403018028678033.324301449736953.045845622
677615.820276408737335.840187923677424.524373966737453.344761614
677179.582702607737522.472341215 676799.90862069737554.786700331
#Sta/Elev= 30
9310.746330.63799409.691323.4467 9430.27314.37399461.415309.86279578.132300.1695
9610.545289.03339666.292282.73599711.882266.53329759.033262.44439781.784256.4159
9896.976251.9487 9930.05242.0167  9963.8236.784910008.09233.890110062.88235.9468
10086.15232.440110155.94243.561310219.97245.215810234.21248.738510360.13256.7954
10498.12258.809210575.02 271.38410607.15269.815310628.26 275.54410680.53280.1164
10823.84283.938210874.39  279.5310894.51284.620311085.27306.619211190.46 312.532
#Mann= 3 , 0 , 0
9310.746  0.0303       09310.746  0.0303       011190.46  0.0303       0
#XS Ineff= 2 , 0
       0                10361.43       0
Bank Sta=9310.746,11190.46
Exp/Cntr=0.3,0.1

Type RM Length L Ch R = 1 ,51042.83,813.899600,813.899600,813.899600
XS GIS Cut Line= 2
678790.395813644736521.841200188676776.506924748736174.618977979
#Sta/Elev= 30
8570.558345.84498636.919346.94038647.067344.20568707.952305.40898738.395296.3452
8829.722 294.8838971.788 284.7689103.706270.19639266.067259.57859357.395250.7324
9367.542246.76329529.903 246.8739661.821241.41399682.116244.05049743.001242.9509
9803.887236.54399885.067238.7985 9915.51236.5489  9956.1226.82849986.542223.8476
10037.28226.150410057.58232.852310067.72242.784110088.02270.867310179.35311.6306
10270.67327.847710493.92346.689110524.36342.587810585.25342.114310614.16344.9124
#Mann= 3 , 0 , 0
8570.558  0.0471       08570.558  0.0471       010614.16  0.0471       0
#XS Ineff= 2 , 0
       0                               0
Bank Sta=8570.558,10614.16
Exp/Cntr=0.3,0.1

Type RM Length L Ch R = 1 ,50228.93,526.622900,526.622900,526.622900
XS GIS Cut Line= 2
678908.451369226735980.174533531677186.229147017735612.118977964
#Sta/Elev= 30
8950.687301.02949036.023300.21619148.507281.36639363.249278.08549393.926269.2906
9526.862262.44159537.088257.68519741.604252.7173 9751.83250.50999772.281235.1598
9782.507231.71859792.733234.02819813.185225.23689932.428239.48339976.798231.4091
9987.023  222.599997.249220.587510027.93223.525810038.15230.0338 10058.6233.6923
10079.06245.656410130.18258.447310191.54265.015810283.57 267.58510324.48273.8318
10385.83300.668210447.18313.687410498.31306.689610559.67305.5914 10711.8315.3242
#Mann= 3 , 0 , 0
8950.687  0.0535       08950.687  0.0535       0 10711.8  0.0535       0
#XS Ineff= 2 , 0
       0                               0
Bank Sta=8950.687,10711.8
Exp/Cntr=0.3,0.1

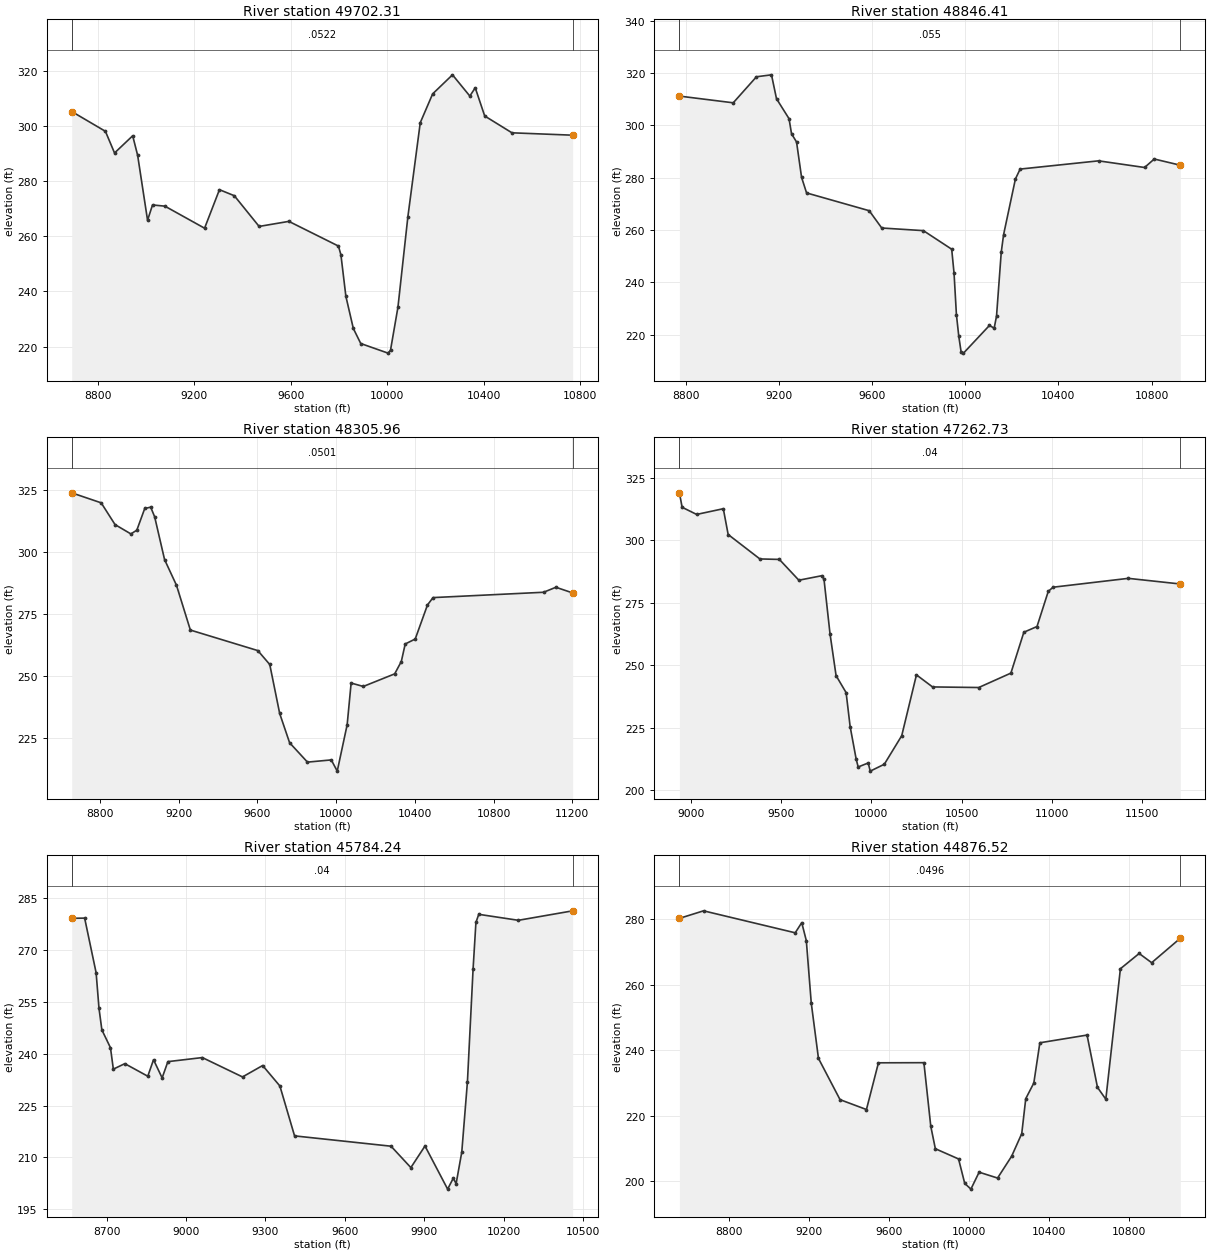
Type RM Length L Ch R = 1 ,49702.31,855.902700,855.902700,855.902700
XS GIS Cut Line= 2
679220.951369226735556.563422427677200.118035883735070.452311307
#Sta/Elev= 30
8691.221305.1852 8831.05298.00368868.934290.14838944.188296.38488964.758 289.305
9005.899265.7617 9026.47271.32089077.896270.8782 9242.46262.88729304.172276.8501
9365.883274.65829468.736263.52969592.159265.36419797.864256.41389808.149253.2206
 9828.72238.19949859.575226.55279890.431221.092410003.57217.611610013.85218.6669
10044.71234.243810085.85266.985510137.28301.1154 10188.7311.571510270.99318.4772
10342.98310.788310365.44313.777710404.69303.561410517.83297.4607 10769.7296.6005
#Mann= 3 , 0 , 0
8691.221  0.0522       08691.221  0.0522       0 10769.7  0.0522       0
#XS Ineff= 2 , 0
       0                               0
Bank Sta=8691.221,10769.7
Exp/Cntr=0.3,0.1

Type RM Length L Ch R = 1 ,48846.41,540.447000,540.447000,540.447000
XS GIS Cut Line= 4
 679652.52992034735169.904756948678741.269820899734809.766034976
 678026.44902426 734695.17644164677597.107175339734815.928836647
#Sta/Elev= 30
8773.597311.13119004.601 308.5649104.273318.51519168.789319.25779190.294310.1181
9244.057302.4997 9254.81296.72139276.315293.5905 9297.82280.08959319.326274.1171
9588.141267.32039641.905260.71159820.558259.7071 9942.09252.60869952.217243.4189
9962.345227.60029972.473219.3533  9982.6213.27659992.728212.888810104.13223.4732
10124.39222.418310134.52227.073310154.77251.4969 10164.9258.225910215.54279.4545
10235.79283.234310572.39286.381310769.76283.840610811.31287.080310923.39284.7096
#Mann= 3 , 0 , 0
8773.597   0.055       08773.597   0.055       010923.39   0.055       0
#XS Ineff= 2 , 0
       0                               0
Bank Sta=8773.597,10923.39
Exp/Cntr=0.3,0.1

Type RM Length L Ch R = 1 ,48305.96,1043.227800,1043.227800,1043.227800
XS GIS Cut Line= 6
679973.877409697734424.305548206679584.988520801734382.638881534
678515.544076353734243.749992639678334.988520771734340.972214878
 678119.71074301734556.249992654677598.877409697734778.472214863
#Sta/Elev= 30
8656.372324.04668806.101319.99718876.502311.2001 8956.96 307.4298987.132308.9357
 9027.36317.70829057.559318.25029077.727314.36479128.147 297.0479188.651286.6671
9259.238268.54269602.094260.23219662.598254.61299713.018234.80329763.437222.9647
9854.193215.12599975.201216.022710005.45211.484810055.87230.249810076.04247.1095
10137.89245.730810297.29250.825310330.97255.820410350.82262.914110401.67264.9187
10463.95278.701710492.24281.671311053.69283.828311116.39285.847911201.69283.5591
#Mann= 3 , 0 , 0
8656.372  0.0501       08656.372  0.0501       011201.69  0.0501       0
#XS Ineff= 2 , 0
       0                               0
Bank Sta=8656.372,11201.69
Exp/Cntr=0.3,0.1

Type RM Length L Ch R = 1 ,47262.73,1478.492400,1478.492400,1478.492400
XS GIS Cut Line= 5
679266.129588097732684.809239313678949.023440063732970.204772562
678724.899878979733216.425022706678097.385439187 734487.82384415
677555.029912252734751.103226151
#Sta/Elev= 30
8934.338319.07038949.572313.27379030.033310.41319178.023312.7018 9204.93302.3617
9380.967292.56979489.147292.37639597.327284.04089725.777285.86019736.928284.3538
9770.383262.48429803.839245.80739859.597238.9723  9881.9225.38679915.356212.3346
9926.507209.17919982.266210.78749993.417207.513810071.48210.264510168.16221.7026
10249.91246.101510339.12 241.26410595.61241.029810774.04246.802710845.99263.1879
10919.01265.479210981.56279.577911008.22281.237311425.64284.787711714.62282.5238
#Mann= 3 , 0 , 0
8934.338    0.04       08934.338    0.04       011714.62    0.04       0
#XS Ineff= 2 , 0
       0                               0
Bank Sta=8934.338,11714.62
Exp/Cntr=0.3,0.1

Type RM Length L Ch R = 1 ,45784.24,907.719900,907.719900,907.719900
XS GIS Cut Line= 4
 678091.92879191732959.962599486677862.749605209733505.627329737
677709.963480711 733865.76605168677388.021289885734717.003030851
#Sta/Elev= 30
8568.124279.21438616.973279.26858660.358263.46018671.204253.1631 8682.05246.9297
8714.589241.75858725.435235.5671 8768.82237.15278855.589 233.5158877.282238.2846
 8909.82233.02988931.513237.73559061.667238.91499213.595233.31169289.634236.6129
 9354.81230.6864 9410.25216.25149774.869213.26359849.708207.07279903.165213.3232
9988.695200.843610010.08204.009110020.77202.423310042.15211.564710063.53231.9175
10084.92264.605610095.61278.0164 10106.3280.363210255.98 278.63510461.25281.3772
#Mann= 3 , 0 , 0
8568.124    0.04       08568.124    0.04       010461.25    0.04       0
#XS Ineff= 2 , 0
       09103.857                       0
Bank Sta=8568.124,10461.25
Exp/Cntr=0.3,0.1

Type RM Length L Ch R = 1 ,44876.52,655.322500,655.322500,655.322500
XS GIS Cut Line= 6
 678118.56014365732648.350905985677675.851810336733108.420350432
677406.754588097733516.406461537677250.504588097733603.212017074
676660.226810306733698.698128238 676087.31014365733863.628683776
#Sta/Elev= 30
8554.201280.30428674.712282.61229132.421275.89539165.064278.99779187.933273.4834
9212.541254.42689248.479237.51289356.292224.89019488.065221.87349547.961 236.154
9774.942236.19429809.261 216.765 9832.14209.88849947.963206.76769978.769 199.309
10009.58197.540210050.65202.715810142.75200.927910213.13207.606710263.41214.4986
10283.52225.201710323.74229.974710353.91242.275110589.57244.6351 10641.6228.6498
10683.23225.025410756.07264.907310849.72269.572310912.16266.753511055.44274.2472
#Mann= 3 , 0 , 0
8554.201  0.0496       08554.201  0.0496       011055.44  0.0496       0
#XS Ineff= 2 , 0
       09653.392        10477.16       0
Bank Sta=8554.201,11055.44
Exp/Cntr=0.3,0.1

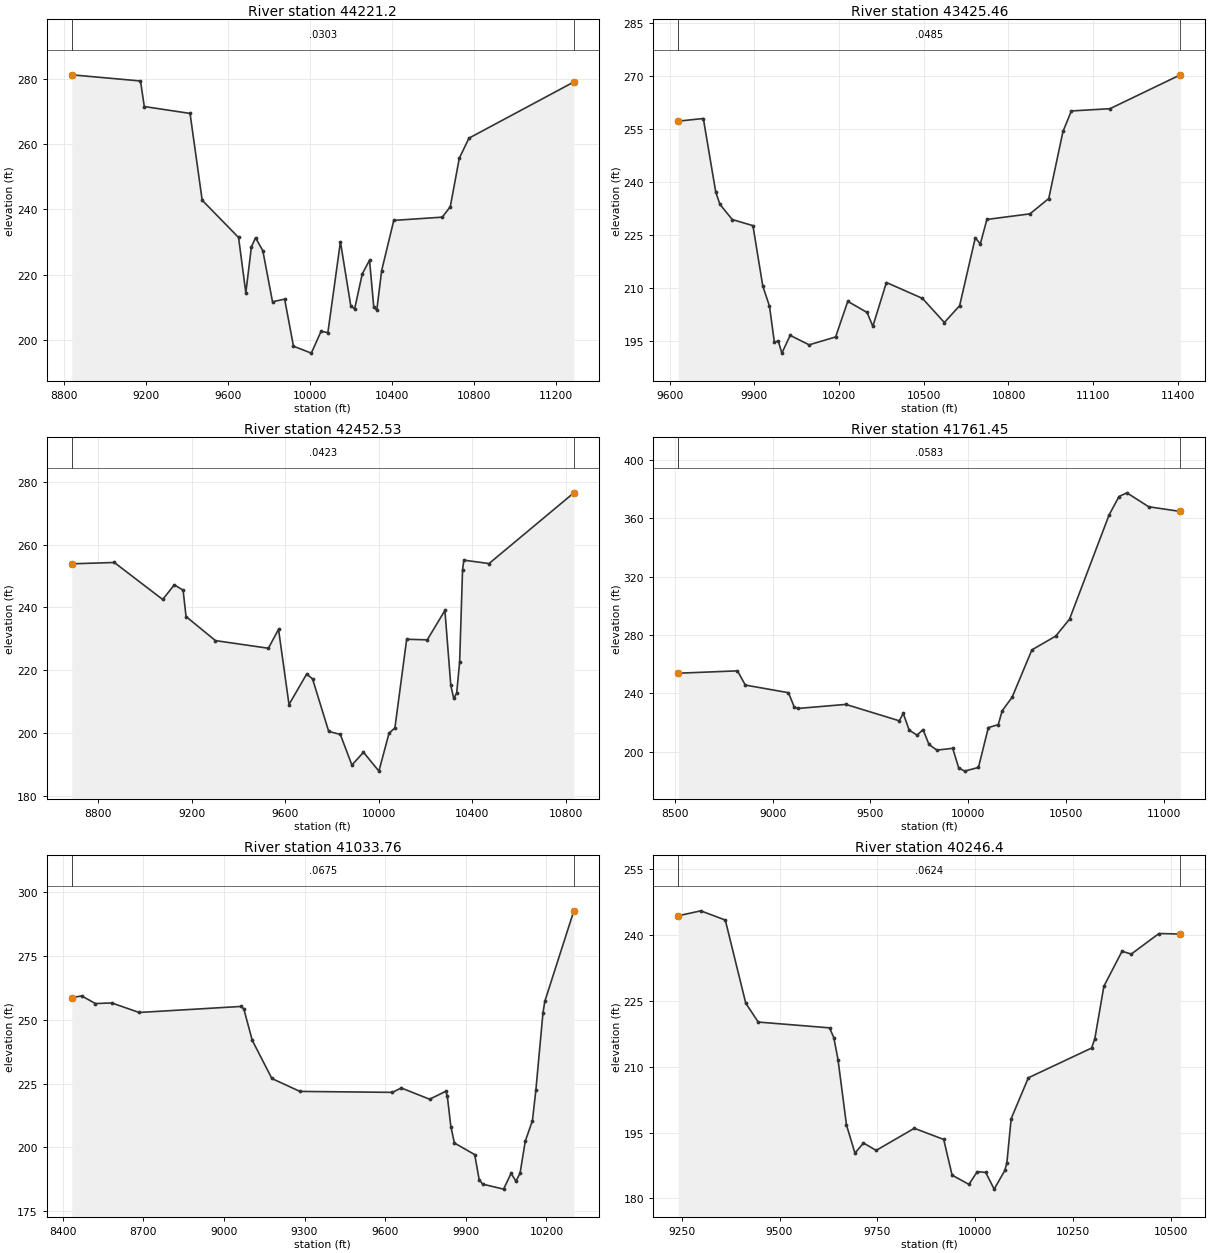
Type RM Length L Ch R = 1 , 44221.2,795.736500,795.736500,795.736500
XS GIS Cut Line= 4
677843.810342342732433.964839995677789.399720162732485.460607424
675921.584836781733669.928582236675770.893675685733736.048173353
#Sta/Elev= 30
8837.551281.16359173.023279.27929191.696271.45949415.007269.34939474.213242.7913
9651.831231.38069687.354214.47599714.531228.50179734.719231.29649770.243227.3525
9817.608211.70399876.814 212.517 9919.93198.112310007.07195.990610054.43202.6304
10087.98202.286310149.16230.063910200.02210.347110218.69209.552810255.73220.2493
10291.26224.433310312.06210.009310326.78209.209810350.46221.271410409.67236.6141
10646.49237.605710685.51240.804210729.38 255.62710776.75261.788211288.74278.9777
#Mann= 3 , 0 , 0
8837.551  0.0303       08837.551  0.0303       011288.74  0.0303       0
#XS Ineff= 2 , 0
       0                10321.67       0
Bank Sta=8837.551,11288.74
Exp/Cntr=0.3,0.1

Type RM Length L Ch R = 1 ,43425.46,972.935200,972.935200,972.935200
XS GIS Cut Line= 3
676915.717687488732036.284714878676019.884354144732994.618048206
675644.884354144733272.395825997
#Sta/Elev= 30
 9630.22257.28619719.134258.02829763.065237.25819777.709233.7837 9821.64229.4681
9894.859227.74349929.614210.69669953.434204.9869 9970.68194.80769984.369195.1518
9997.366191.703910026.65 196.73310093.88194.047510187.73196.280510230.77206.3401
10299.21203.196710319.53199.283110367.65211.668210495.25207.185710572.99200.3571
10627.05205.1296 10682.5224.330110700.27222.557610723.56229.494210875.99231.0735
 10942.7235.4033 10993.1254.367511022.81260.1617 11159.7260.805611408.73270.3761
#Mann= 3 , 0 , 0
 9630.22  0.0485       0 9630.22  0.0485       011408.73  0.0485       0
#XS Ineff= 2 , 0
       0                               0
Bank Sta=9630.22,11408.73
Exp/Cntr=0.3,0.1

Type RM Length L Ch R = 1 ,42452.53,691.082100,691.082100,691.082100
XS GIS Cut Line= 4
677005.995465249731744.618048206676644.884354115 731779.34027043
675478.217687488 732668.22915931675246.283575445732883.128562585
#Sta/Elev= 30
 8687.72 253.8978869.551254.31819076.336242.51749125.782247.19149163.498245.4901
9176.069237.08139301.787 229.408 9528.08226.9709 9571.35 233.0039616.082209.0267
9691.513218.73429716.656217.19629785.857200.43499835.358199.50279884.859 189.731
9934.361193.803310000.36 187.78710043.52199.886210068.67201.557310118.95229.8338
10206.96229.655310282.39239.021210307.53215.1348 10320.1210.979710332.67212.6859
10345.25222.496110357.82252.078210363.37255.061110470.96253.978410833.39276.5294
#Mann= 3 , 0 , 0
 8687.72  0.0423       0 8687.72  0.0423       010833.39  0.0423       0
#XS Ineff= 2 , 0
       0                10136.13       0
Bank Sta=8687.72,10833.39
Exp/Cntr=0.3,0.1

Type RM Length L Ch R = 1 ,41761.45,727.689800,727.689800,727.689800
XS GIS Cut Line= 3
677026.828798592731702.951381549676443.495465219 731654.34027043
674485.162131935731959.895825997
#Sta/Elev= 30
8517.541 253.7698820.416255.38978860.555245.62949081.317240.38729111.495230.2987
9131.737229.6023 9374.64232.35939647.907221.10059668.149226.19219698.512214.6934
9738.996211.23779769.359215.11539799.722204.86089840.206200.97679921.174 202.215
9951.537188.8264  9981.9186.553410052.75189.090610103.35216.447810153.96218.4735
 10174.2228.0292 10224.8237.268610326.01269.796110447.47279.211110518.31290.8334
10720.73362.407910771.34375.062610811.82377.587610923.15  368.0311084.92364.8063
#Mann= 3 , 0 , 0
8517.541  0.0583       08517.541  0.0583       011084.92  0.0583       0
#XS Ineff= 2 , 0
       0                               0
Bank Sta=8517.541,11084.92
Exp/Cntr=0.3,0.1

Type RM Length L Ch R = 1 ,41033.76,787.355300,787.355300,787.355300
XS GIS Cut Line= 4
677311.551020771731709.895825997676811.551020771731619.618048221
676130.995465219 731418.22915931675637.939909667730994.618048206
#Sta/Elev= 30
8434.182258.69818471.324259.32268522.133256.34378583.103256.5784 8684.72252.8461
9064.267255.21499074.243254.23419105.529241.97199178.529 227.0029282.816221.9395
9626.961221.56759659.899223.2871 9765.37218.88199825.747221.98649831.289220.0917
9844.473208.19739857.657201.74269933.163197.19539949.944187.33149963.128185.6218
10040.58 183.674 10068.6189.867810086.61 186.78410101.96189.936910121.33202.4441
   10148210.513810160.89222.587810187.25 252.77610194.03257.200810302.03292.6516
#Mann= 3 , 0 , 0
8434.182  0.0675       08434.182  0.0675       010302.03  0.0675       0
#XS Ineff= 2 , 0
       0                               0
Bank Sta=8434.182,10302.03
Exp/Cntr=0.3,0.1

Type RM Length L Ch R = 1 , 40246.4,497.789100,497.789100,497.789100
XS GIS Cut Line= 6
677050.705320282730838.415124206676884.007776993730790.053009075
676788.650995685730755.495979036676232.485296027730528.850413602
676096.808950985730459.549689435675879.198294504730325.684149035
#Sta/Elev= 30
9240.962244.39799298.502245.52689361.251243.42739413.541224.50249445.432220.1839
9627.759218.86269638.597216.65959649.435 211.631 9671.11196.72319692.786190.3126
9714.462192.62829746.975190.94199844.516195.98029919.657193.43329941.125 185.293
 9984.06183.206510005.54186.100110027.07185.9184 10048.6182.115710075.91186.3651
 10081.2188.1721 10092.1198.165810135.98207.481410297.66214.260110305.93216.3662
10329.14228.337310375.57236.3219 10399.1235.671110469.96240.359710524.53240.2334
#Mann= 3 , 0 , 0
9240.962  0.0624       09240.962  0.0624       010524.53  0.0624       0
#XS Ineff= 2 , 0
       09328.837                       0
Bank Sta=9240.962,10524.53
Exp/Cntr=0.3,0.1

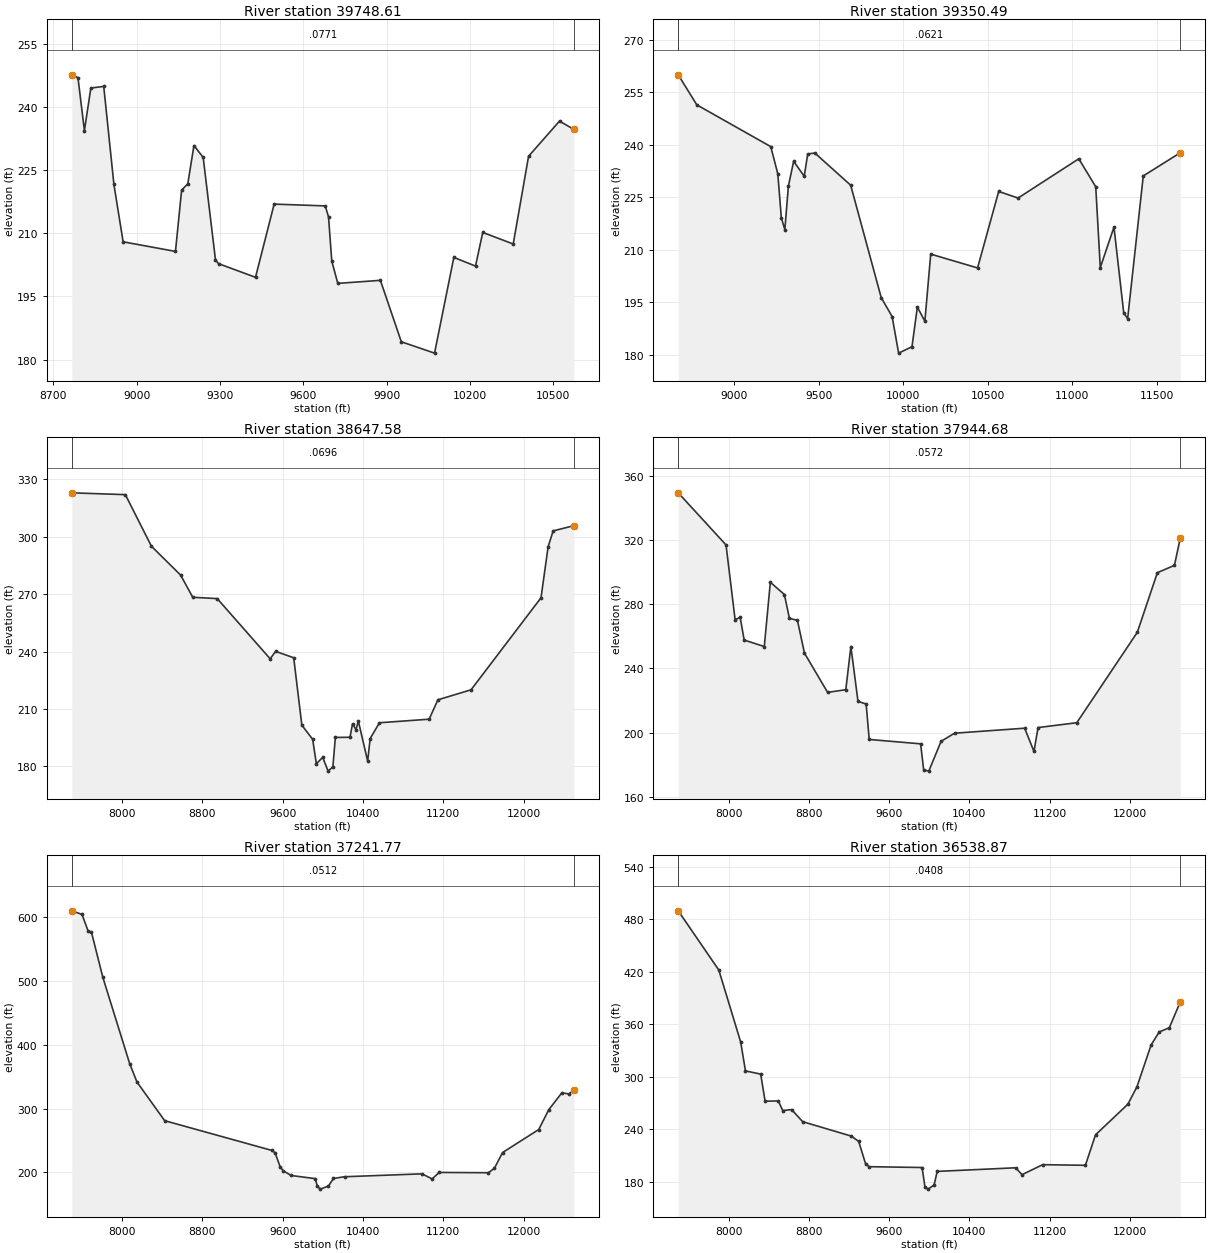
Type RM Length L Ch R = 1 ,39748.61,398.126100,398.126100,398.126100
XS GIS Cut Line= 6
677651.828798562730744.618048206677019.033971101730442.187933758
676794.635946453730313.847513422676659.526577353730214.931624234
676377.869486511729968.547276124676133.835552514729784.456825539
#Sta/Elev= 30
8766.409 247.6498788.714246.97318811.905234.40448835.095244.51168881.476244.8976
8918.062221.63858951.312207.9865 9139.73205.70649161.897220.26589184.063221.7569
 9206.23  230.85 9239.48228.04039283.814203.66899294.897202.79619427.898199.5536
9495.001216.9424 9679.03216.51559690.762213.88789702.493203.3942 9724.18198.1124
9877.459198.83379952.785184.244710072.43181.546810141.92204.287210219.94202.2166
10245.95210.215510355.69207.467110410.97228.311810522.29 236.65710573.93234.6888
#Mann= 3 , 0 , 0
8766.409  0.0771       08766.409  0.0771       010573.93  0.0771       0
#XS Ineff= 2 , 0
       09615.828                       0
Bank Sta=8766.409,10573.93
Exp/Cntr=0.3,0.1

Type RM Length L Ch R = 1 ,39350.49,702.904000,702.904000,702.904000
XS GIS Cut Line= 4
678020.469698489730382.819208354677216.303031832730149.485875025
676582.969698459729632.819208369675445.469698489728974.485875025
#Sta/Elev= 30
8669.604260.02838779.424251.45059216.747239.51499258.397231.73229279.221219.1757
9300.046215.77949320.871 228.2199352.109235.31869414.583231.04559435.408 237.404
9477.058237.69469689.297228.48849869.973196.35469934.501190.95469972.804 180.507
 10051.9182.336510083.54193.667410128.08189.621110162.64208.799210439.71204.8512
10564.57226.702910679.28 224.82211038.29236.036611138.44228.039311165.38204.9626
11246.26216.509111304.03191.988911327.14190.363411419.57231.140911638.56237.7692
#Mann= 3 , 0 , 0
8669.604  0.0621       08669.604  0.0621       011638.56  0.0621       0
#XS Ineff= 2 , 0
       09735.234                       0
Bank Sta=8669.604,11638.56
Exp/Cntr=0.3,0.1

Type RM Length L Ch R = 1 ,38647.58,702.904100,702.904100,702.904100
XS GIS Cut Line= 6
679635.668843932 729708.51946787678783.689684985729768.330361415
 678033.30887726729656.597787867677510.394948003729443.067913444
676252.630312469 728692.95461298 674939.60392329728400.086194874
#Sta/Elev= 30
7499.066322.9512 8032.79322.00268292.905295.01828583.397279.95048704.197268.3543
8948.029267.65769475.489236.19999530.059240.08569710.071236.73669791.131201.5141
9899.021194.08029935.794181.32099999.049184.702810052.77177.474910100.35179.7316
10125.02195.087610270.67195.1723 10296.2202.194110330.64199.133510354.13203.6625
10446.92182.704810471.58 194.47410564.18202.756711059.32204.621111146.61214.7558
11476.81219.986212173.94268.094112244.55294.7216 12294.8303.048312500.96305.7798
#Mann= 3 , 0 , 0
7499.066  0.0696       07499.066  0.0696       012500.96  0.0696       0
#XS Ineff= 2 , 0
       09697.643        11284.77       0
Bank Sta=7499.066,12500.96
Exp/Cntr=0.3,0.1

Type RM Length L Ch R = 1 ,37944.68,702.904000,702.904000,702.904000
XS GIS Cut Line= 6
679975.752335821728723.149038717679226.070561078728818.737594944
678446.656534909728803.441360011677405.602721533728602.830288013
676270.479782708728301.364004812675046.473478625 728211.86122282
#Sta/Elev= 30
7499.036349.36957975.159316.92798065.655270.38068115.898271.79018156.016257.6798
 8356.43253.62128416.483293.66658556.509286.04288606.509 271.2048686.529269.9192
8756.562  249.538987.204225.07199168.475226.75589218.986253.64429289.897219.4858
9371.152217.83649401.622195.75299913.642193.03699944.211176.78329995.159176.0328
10117.77194.606810252.36199.6537 10950.4202.775311042.98188.266211083.87203.1717
11469.69206.188112072.32262.467712272.42 299.62412442.43304.200212500.96321.3742
#Mann= 3 , 0 , 0
7499.036  0.0572       07499.036  0.0572       012500.96  0.0572       0
#XS Ineff= 2 , 0
       09602.592                       0
Bank Sta=7499.036,12500.96
Exp/Cntr=0.3,0.1

Type RM Length L Ch R = 1 ,37241.77,702.904100,702.904100,702.904100
XS GIS Cut Line= 6
680162.919509955727607.980117214679215.789231877727841.898732041
678451.990406056727953.126315029677961.265437891 727970.80258938
677261.940217999727924.059401613675205.837185775728061.912227297
#Sta/Elev= 30
7499.048 610.1737600.967604.55017663.315 577.908  7694.4577.10777808.378505.8758
8076.511 370.1538148.449  341.598424.747280.87099494.661234.12879524.689230.4363
9574.699208.63759604.705202.38939684.713194.88689925.105189.94629945.219177.9313
9975.439 173.49310056.22178.324110106.48190.282710216.89192.921410988.63197.4707
11088.97 189.56211159.18199.679411650.22199.220711710.31206.306111790.43230.8548
12150.96266.991812251.15298.125312381.48324.629412451.66322.878112500.95328.7671
#Mann= 3 , 0 , 0
7499.048  0.0512       07499.048  0.0512       012500.95  0.0512       0
#XS Ineff= 2 , 0
       0                               0
Bank Sta=7499.048,12500.95
Exp/Cntr=0.3,0.1

Type RM Length L Ch R = 1 ,36538.87,702.904000,702.904000,702.904000
XS GIS Cut Line= 6
679631.731834917726165.494640811677966.323369832726951.238455053
 677174.98904807727542.511733145676899.945548977727690.700353189
 676318.06898011727852.148795566675076.204342308  728010.7902649
#Sta/Elev= 30
7499.034489.75927903.586422.00338120.712339.97038168.962306.81858320.494303.1555
8364.448272.20818496.309272.46538540.263261.46168628.186262.62038738.447248.7931
9223.296232.29279296.835226.22549365.512200.63759400.172 197.3499928.576196.4024
9956.919174.24099987.535171.698210047.55176.286810079.14191.964810861.37196.0945
10923.78188.207911129.61 199.64311555.48198.929711656.35233.792311978.65268.7497
12069.26288.7666 12210.2336.479912290.74351.350912391.41356.105612500.94385.8298
#Mann= 3 , 0 , 0
7499.034  0.0408       07499.034  0.0408       012500.94  0.0408       0
#XS Ineff= 2 , 0
       0                               0
Bank Sta=7499.034,12500.94
Exp/Cntr=0.3,0.1