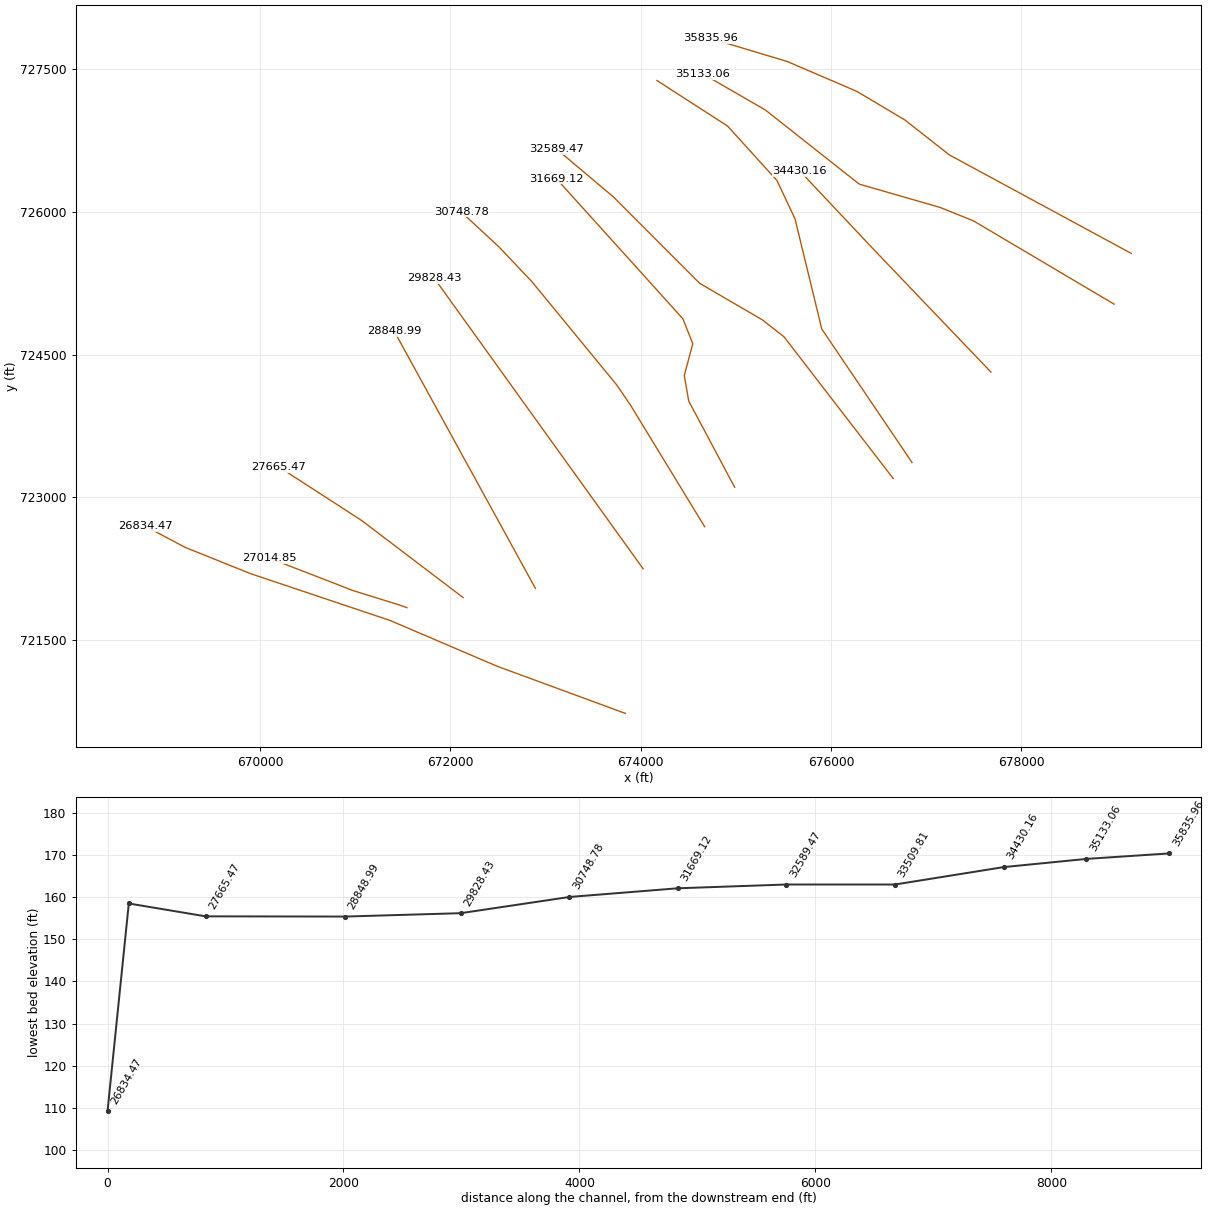
HEC-RAS study 3955_ras.prj: 3955

--- 3955_ras.g01 (geometry) --- (continued)

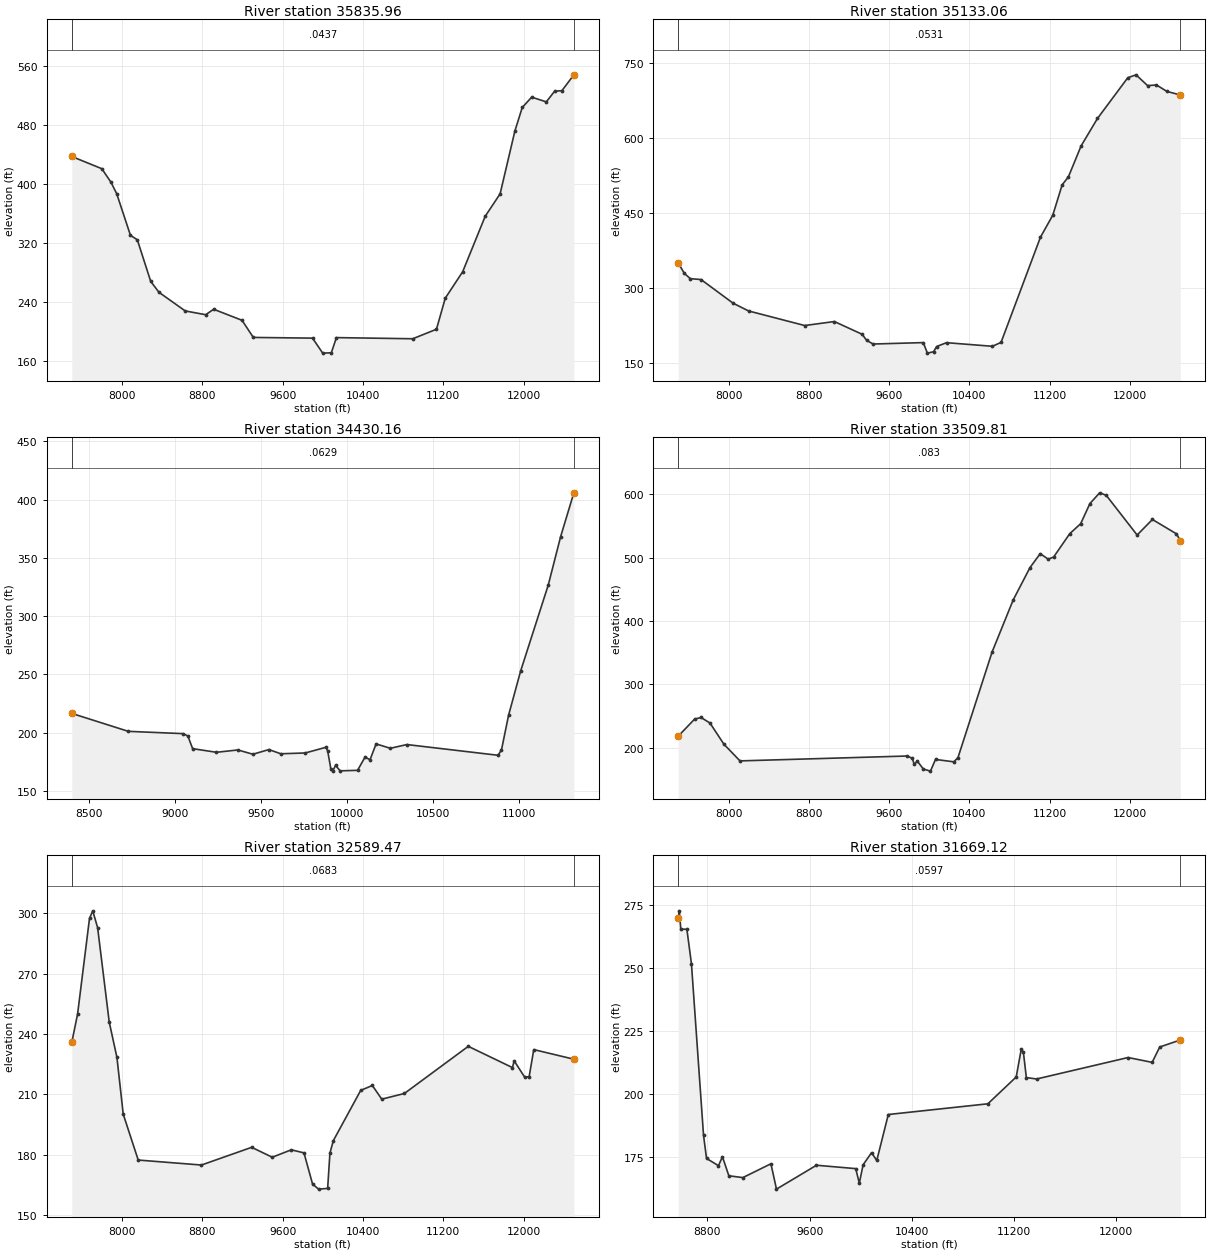
Type RM Length L Ch R = 1 ,35835.96,702.904100,702.904100,702.904100
XS GIS Cut Line= 6
679156.490851717725564.984790324677245.381245207726599.965097074
676774.212463015726969.673533421676273.332312556 727267.38525373
675542.384857409727581.600071216674730.381620297727825.472670794
#Sta/Elev= 30
 7499.08437.20537798.474420.64557889.847402.22267946.863386.6461  8083.7330.2474
8152.119324.15488285.702267.6655 8368.28 252.843 8629.32227.60258833.172222.4683
 8912.35229.88579195.126 214.8999307.806191.62379897.655190.6921    9999170.3298
10084.81 170.80410135.64191.392510896.18189.828111132.26202.745411220.06244.9202
11393.55280.818111618.12 356.15411766.33386.508611913.57471.783411986.98503.7464
12080.92517.736212226.67511.364912309.78 525.82612382.31526.588712500.93548.0532
#Mann= 3 , 0 , 0
 7499.08  0.0437       0 7499.08  0.0437       012500.93  0.0437       0
#XS Ineff= 2 , 0
       0                               0
Bank Sta=7499.08,12500.93
Exp/Cntr=0.3,0.1

Type RM Length L Ch R = 1 ,35133.06,702.904000,702.904000,702.904000
XS GIS Cut Line= 6
678976.710777416725031.381688725677498.214330481725907.073503506
677148.535439454726047.694573696  676297.4726126726293.482110214
675311.331260371727072.083385139674655.179639948727451.351381175
#Sta/Elev= 30
7499.046349.47247560.364328.55037619.652318.08347726.373316.29288045.413 268.992
8199.537253.45988759.081 224.2729054.733232.2598 9331.74206.6757 9375.06194.7856
9440.162 187.2499940.177190.08969981.174169.026510042.65171.796910073.39 182.235
10171.62189.944110628.31182.722910715.01190.510211107.86401.209411230.42445.1113
11323.68505.825511386.06521.885911513.05584.000411675.86638.836411977.57720.2683
12059.61726.114412175.04704.551812263.69705.746212367.52692.901512500.94685.7542
#Mann= 3 , 0 , 0
7499.046  0.0531       07499.046  0.0531       012500.94  0.0531       0
#XS Ineff= 2 , 0
       0                               0
Bank Sta=7499.046,12500.94
Exp/Cntr=0.3,0.1

Type RM Length L Ch R = 1 ,34430.16,920.344600,920.344600,920.344600
XS GIS Cut Line= 3
 677682.00946781724317.703864768 676438.79636851725617.897564441
675673.223242283726430.893698707
#Sta/Elev= 30
8401.707216.58828730.024201.20889048.245199.23699075.917197.20779103.588186.3632
9241.945 183.2399366.467185.2436 9453.68181.56869546.331185.5787 9615.51181.9679
9757.547 182.6529878.388187.55869887.775184.4133 9906.06 169.1339916.715167.0796
9933.731172.03079960.125167.326310061.41167.756510104.82179.133710133.76176.8192
10168.94190.437210251.58186.677510347.73189.874510877.15180.677410897.17185.2974
10938.38215.074311008.43253.006211168.88326.770111240.56368.222911317.34405.8209
#Mann= 3 , 0 , 0
8401.707  0.0629       08401.707  0.0629       011317.34  0.0629       0
#XS Ineff= 2 , 0
       0                               0
Bank Sta=8401.707,11317.34
Exp/Cntr=0.3,0.1

Type RM Length L Ch R = 1 ,33509.81,920.344700,920.344700,920.344700
XS GIS Cut Line= 6
676852.297876107723367.802925274675903.609680723724770.663950546
675622.959474261 725927.49787273675433.053651014726331.035464438
674913.571372756726903.669046968 674171.02156329727382.429193191
#Sta/Elev= 30
7499.095 218.1917662.172245.11357726.276247.67217815.238238.93117954.073205.5129
8114.285179.11459779.616186.82989830.261183.28849850.455173.56819880.746178.7218
  9941.3166.241510011.73 162.95910062.07181.408110245.06177.656210285.94184.3422
10626.09351.212910835.79433.268311003.28484.436411105.46506.4537 11184.8497.7419
11238.74501.080311398.99537.911911508.08553.725311600.55585.616611697.45602.5213
11763.03598.616412070.73535.871112223.03560.425312462.43537.749312500.92527.1687
#Mann= 3 , 0 , 0
7499.095   0.083       07499.095   0.083       012500.92   0.083       0
#XS Ineff= 2 , 0
       0                               0
Bank Sta=7499.095,12500.92
Exp/Cntr=0.3,0.1

Type RM Length L Ch R = 1 ,32589.47,920.344600,920.344600,920.344600
XS GIS Cut Line= 6
676654.422976263723199.552811385675506.708568066724688.749360664
 675279.80310893724866.493760975674619.921777607725251.086350039
673711.851236102 726160.68809435 673115.09638773 726662.90046209
#Sta/Elev= 30
7499.089235.78927556.964249.8865 7675.82297.42967708.123301.18627756.576292.8182
7872.257245.93657949.017228.37228011.778200.17878161.136177.39918790.989 174.928
9291.438183.7251 9496.12178.80189686.481182.48399812.327 180.9659898.207165.4451
 9958.16 162.95910048.16 163.31610070.99180.847910105.23187.081210377.59212.0028
10493.53214.436310587.31207.643910812.39210.458511449.32233.882511889.08223.3279
11906.68226.670212012.96218.418912055.85218.883512101.63232.265612500.92227.4928
#Mann= 3 , 0 , 0
7499.089  0.0683       07499.089  0.0683       012500.92  0.0683       0
#XS Ineff= 2 , 0
       0                10273.71       0
Bank Sta=7499.089,12500.92
Exp/Cntr=0.3,0.1

Type RM Length L Ch R = 1 ,31669.12,920.344700,920.344700,920.344700
XS GIS Cut Line= 6
674987.643689811723108.034309536674505.830882728724012.513487726
674458.894321442724280.880685478674547.944619864724615.613712296
 674444.30921188724877.718501806 673113.73893714726351.637570366
#Sta/Elev= 30
8571.535269.98978579.807272.79258591.683265.50778639.188265.44778674.816251.7832
8769.492 183.4798792.979174.26648886.379171.39738917.483174.94428967.637167.3723
 9077.27166.64849296.873172.15329340.377162.06189653.525171.56489960.549170.2183
9988.695164.427210018.23171.732210084.28176.564210125.26173.452610215.55191.7529
10994.74196.013811216.54206.686311255.87217.679911272.48216.628511295.84 206.455
11375.89 205.881   12092 214.42512280.34212.502812339.66218.604512500.76221.4117
#Mann= 3 , 0 , 0
8571.535  0.0597       08571.535  0.0597       012500.76  0.0597       0
#XS Ineff= 2 , 0
       08626.533        10390.65       0
Bank Sta=8571.535,12500.76
Exp/Cntr=0.3,0.1

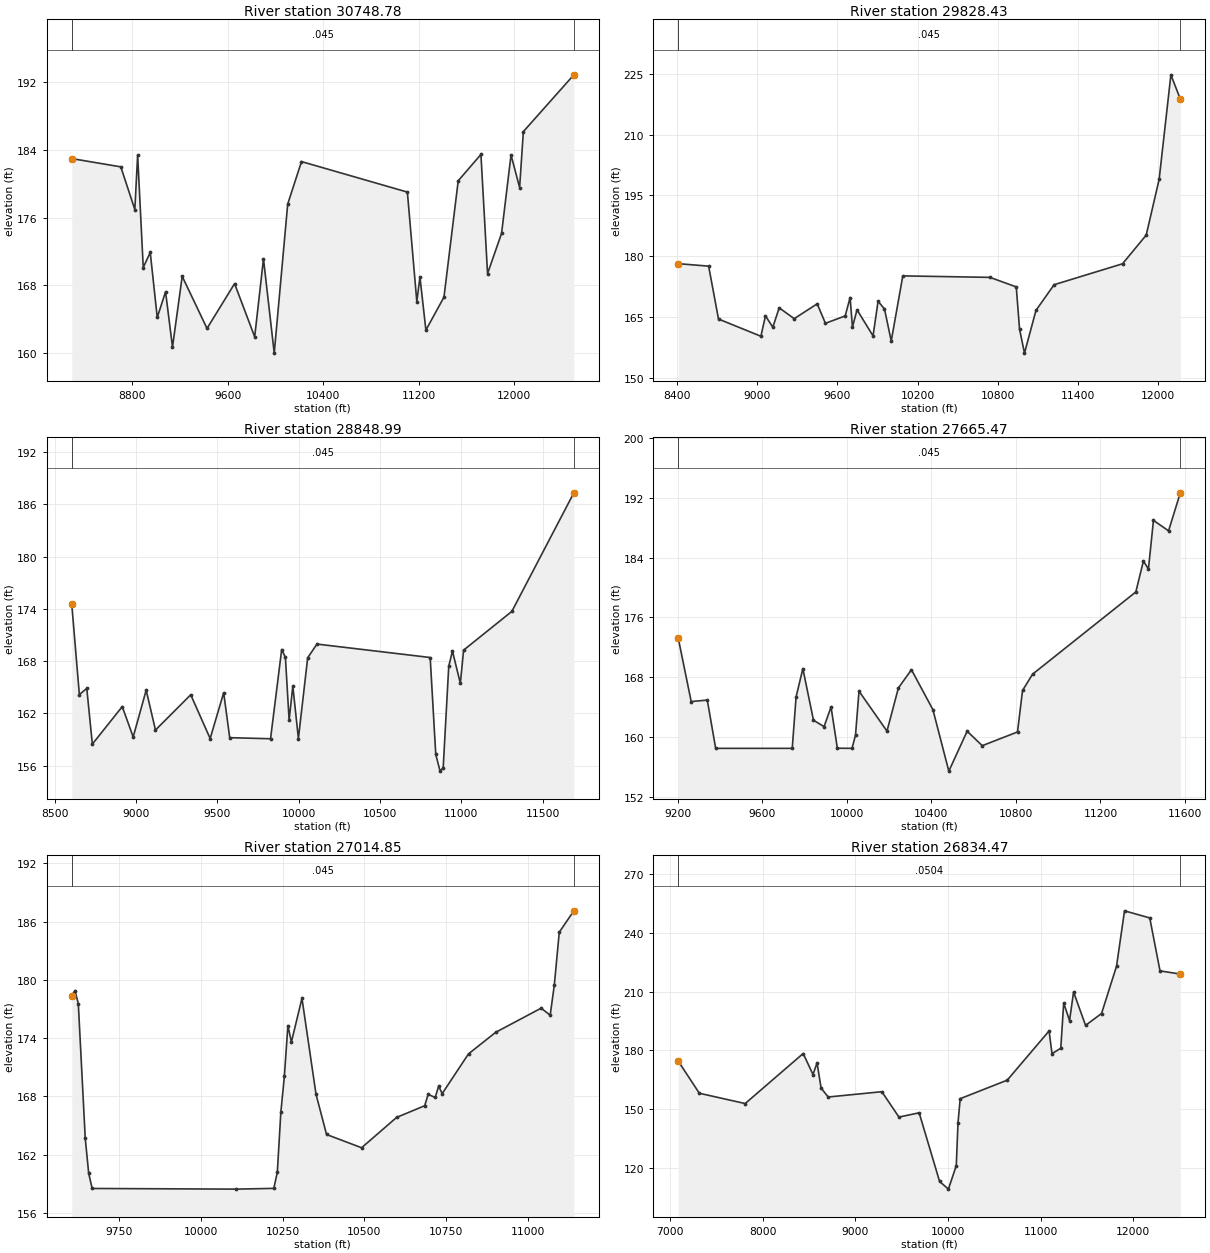
Type RM Length L Ch R = 1 ,30748.78,920.344600,920.344600,920.344600
XS GIS Cut Line= 6
674673.359527349722691.674294248673892.885518759723971.471136481
673748.572353929724182.641202942 672854.65193814725271.308391809
672510.538216621725633.963799044672112.928934902 726002.28588669
#Sta/Elev= 30
8294.749182.99918705.483182.02118823.118176.9731 8846.59  183.418893.535170.1216
8952.216171.90129010.823164.21039080.525167.25419138.609  160.719219.928169.0735
9427.736162.91799658.743168.21329827.136161.92629900.853171.13659990.944159.9977
10103.87177.624810219.33182.6448 11106.3179.036611185.52166.080711211.67 169.007
11261.49162.718411412.92166.617211532.36180.378911722.62183.489311778.07169.4027
11895.43 174.15511974.74 183.42412046.61179.579212077.95186.188112500.96192.9022
#Mann= 3 , 0 , 0
8294.749   0.045       08294.749   0.045       012500.96   0.045       0
#XS Ineff= 2 , 0
       08848.617        10263.56       0
Bank Sta=8294.749,12500.96
Exp/Cntr=0.3,0.1

Type RM Length L Ch R = 1 ,29828.43,979.442800,979.442800,979.442800
XS GIS Cut Line= 2
 674026.19688046722250.174014434671832.489102393725302.289183915
#Sta/Elev= 30
8408.701178.20058636.315177.58848710.205164.55719027.574160.31959061.842165.3611
9116.601162.53669164.646 167.3219276.697164.65289449.107 168.3089510.682163.5076
9658.463165.32529695.408169.85049712.933162.58049747.201166.83219867.139160.4008
9904.764168.94629952.808167.034910003.28159.147210089.88175.189910742.19174.8267
10939.23172.475910963.86162.0654 11000.8156.161411087.01166.702911222.47173.0127
11734.74178.172911912.11185.237912008.88198.963312096.84224.721812167.39218.7515
#Mann= 3 , 0 , 0
8408.701   0.045       08408.701   0.045       012167.39   0.045       0
#XS Ineff= 2 , 0
       08628.229        10718.91       0
Bank Sta=8408.701,12167.39
Exp/Cntr=0.3,0.1

Type RM Length L Ch R = 1 ,28848.99,1183.516300,1183.516300,1183.516300
XS GIS Cut Line= 2
 672894.28926602 722044.12378177 671409.31201908724748.903767243
#Sta/Elev= 30
8605.195174.51378651.827164.15518697.459164.85998731.683158.46428915.401162.7716
8982.658159.28159062.514164.66179119.554  160.089336.306164.13239455.651159.1043
9538.766 164.3669575.874159.2029 9826.85159.07939895.298169.32549918.114168.4301
 9940.93161.22329963.746165.1291 9997.97159.106810055.01168.377310112.05169.9535
10807.94168.410610842.16157.286910868.61155.359610887.79155.732610922.02167.4098
10944.83169.148710993.29165.446311013.28169.258211309.89173.708811690.81187.3274
#Mann= 3 , 0 , 0
8605.195   0.045       08605.195   0.045       011690.81   0.045       0
#XS Ineff= 2 , 0
       0 8609.62        10921.16       0
Bank Sta=8605.195,11690.81
Exp/Cntr=0.3,0.1

Type RM Length L Ch R = 1 ,27665.47,650.619700,650.619700,650.619700
XS GIS Cut Line= 3
672134.535502613721947.941940099671064.650772095722760.106371179
670198.385581106723320.632379472
#Sta/Elev= 30
9202.534173.23349263.824164.73389340.055 164.9269379.596158.46429741.811158.4642
 9759.99165.34389792.031169.14669842.251162.23279892.301161.37069925.379164.0023
9955.245158.482310024.61158.464210041.15 160.24510057.69166.1223   10190 160.773
10244.01166.556210305.77 168.99410407.22163.646510482.55155.412810569.17160.7595
10640.63158.822210807.39160.657710831.21166.213410878.85168.4023 11367.2179.4159
11402.93183.545811426.75182.489911450.57188.999411522.04 187.60111577.56192.6915
#Mann= 3 , 0 , 0
9202.534   0.045       09202.534   0.045       011577.56   0.045       0
#XS Ineff= 2 , 0
       0                               0
Bank Sta=9202.534,11577.56
Exp/Cntr=0.3,0.1

Type RM Length L Ch R = 1 ,27014.85,180.384400,180.384400,180.384400
XS GIS Cut Line= 6
 671543.88713787721841.753482128671525.572074711721848.196923763
671445.446676314721875.988363326670964.891120732722025.293918893
670832.252231836722078.071696714670099.266120762722361.057807788
#Sta/Elev= 30
9604.849178.38619614.631178.9016 9624.87177.55889646.038163.70489656.623160.0834
9667.207158.527310107.46158.459610222.93158.5368 10233.7 160.19910244.46166.3948
10255.22170.068410265.98175.306710276.75 173.61210309.03178.109210352.08168.2228
10384.25164.087310491.45162.721810598.64165.8475 10684.4167.046710695.12168.2194
10716.55 167.89910727.27169.075110737.99168.296310818.52172.390510901.82174.6127
11040.64177.094711068.41176.372711081.01179.477811096.17184.919611140.76187.1214
#Mann= 3 , 0 , 0
9604.849   0.045       09604.849   0.045       011140.76   0.045       0
#XS Ineff= 2 , 0
       09619.886        10330.64       0
Bank Sta=9604.849,11140.76
Exp/Cntr=0.3,0.1

Type RM Length L Ch R = 1 ,26834.47,341.788100,341.788100,341.788100
XS GIS Cut Line= 6
673839.373215705720730.726152718672494.394366086721225.086850449
671364.309439719721707.986576721669895.696870148722200.842998371
669211.461628437 722476.31432946668797.887973666722694.979892924
#Sta/Elev= 30
7089.794174.57697317.585158.16757812.181152.90788437.913 178.4588544.019167.7398
 8587.78173.68448631.541160.80098708.122156.25069286.931158.95759471.483146.0057
9689.368148.18699910.022113.135410005.29109.214610089.97121.225110108.81 143.128
10132.31155.390910639.92164.853611091.41189.983211122.98178.379611217.69181.1592
11249.26204.248611312.27195.262811355.79209.846511485.15192.819111657.63198.8852
11819.33223.032311905.57251.309212177.84247.682212288.48220.654912507.52219.0142
#Mann= 3 , 0 , 0
7089.794  0.0504       07089.794  0.0504       012507.52  0.0504       0
#XS Ineff= 2 , 0
       09807.323        10311.09       0
Bank Sta=7089.794,12507.52
Exp/Cntr=0.3,0.1