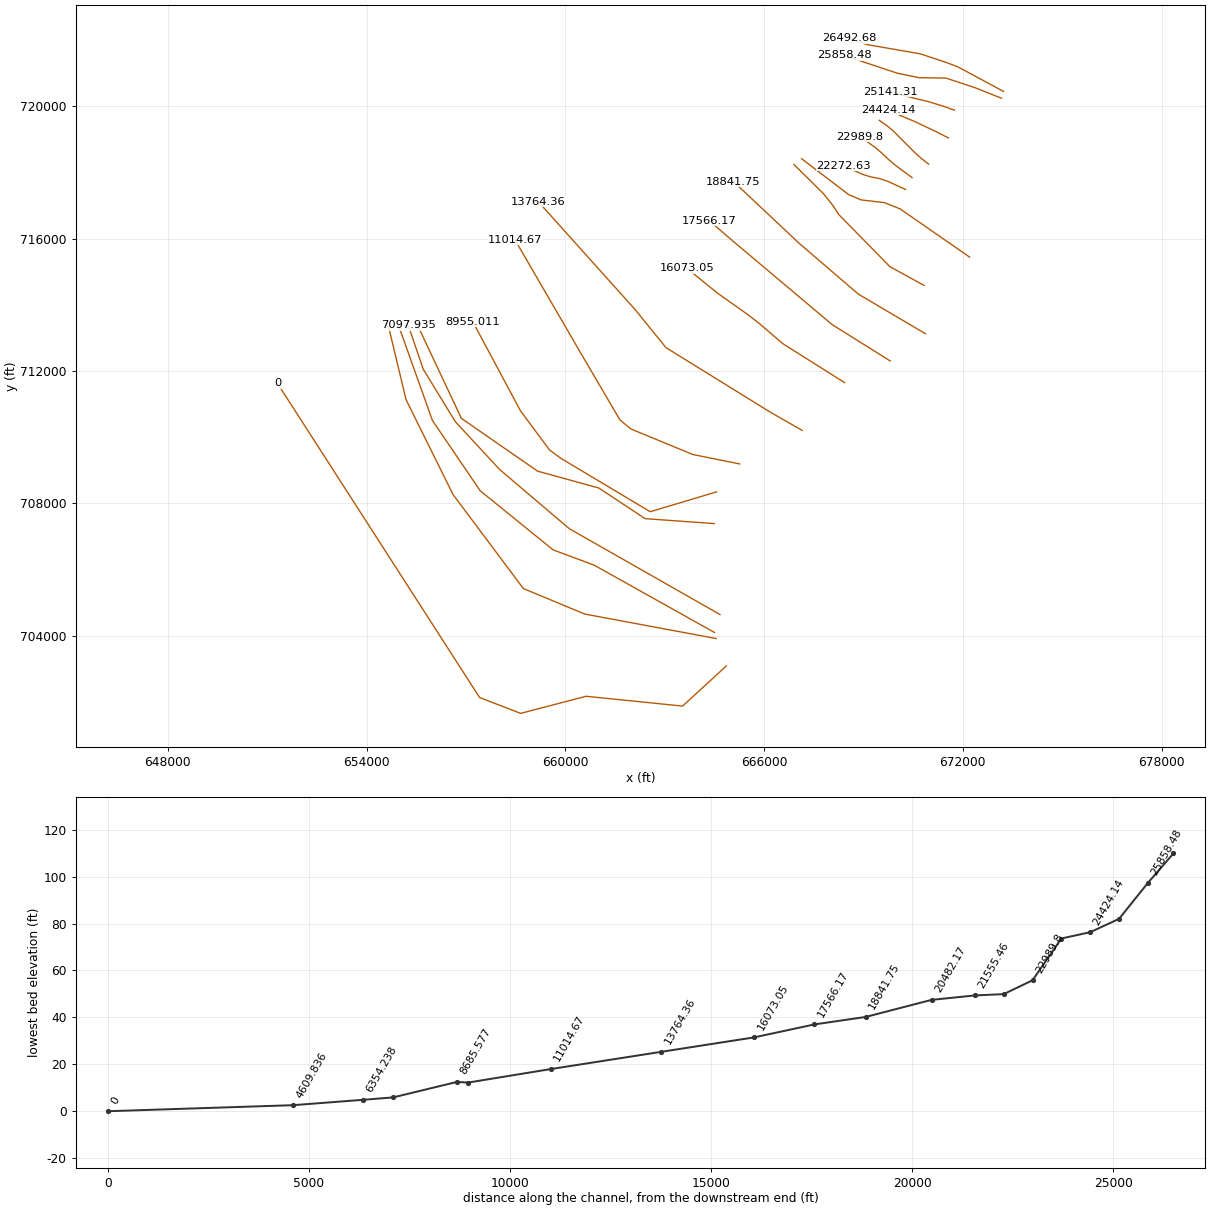
HEC-RAS study 3955_ras.prj: 3955

--- 3955_ras.g01 (geometry) --- (continued)

Type RM Length L Ch R = 3 ,26657.65,,,
BEGIN DESCRIPTION:
END DESCRIPTION:
Bridge Culvert--1,0,-1,-1, 0
Deck Dist Width WeirC Skew NumUp NumDn MinLoCord MaxHiCord MaxSubmerge Is_Ogee
100.894050,140.000000,2.6,0, 60, 60, , , 0.95, 0, 0,0,,
 9330.21 9344.68 9355.25 9365.81 9384.78 9429.18 9471.43 9492.55 9540.13 9545.36
 9555.92 9566.49 9571.20 9577.05 9587.61 9602.27 9619.30 9629.86 9650.98 9661.54
 9672.11 9695.48 9714.35 9724.92 9767.16 9788.29 9827.32 9827.3210299.0610305.83
10314.3210314.3210316.8810337.5110348.0710400.5910447.4210481.0810505.3210536.74
10568.1610620.5210631.0010662.4210682.9910704.3110756.6710788.0910798.5710817.61
10840.4610851.2610871.8810892.8210913.7710945.1910966.1310997.5511018.5011085.16
  170.08  170.16  170.04  170.16  169.96  169.98  169.63  169.85  169.44  169.53
  165.79  158.52  162.44  169.80  170.06  169.96  170.06  169.91  170.99  171.35
  171.53  171.65  171.89  172.24  172.62  173.00  173.12  173.12  174.72  174.07
  173.63  173.63  173.52  174.00  174.02  174.86  175.13  175.94  176.00  175.70
  175.93  176.57  176.53  176.81  176.85  177.35  178.14  178.42  178.35  178.71
  178.79  179.04  178.93  179.29  179.30  179.67  179.50  180.04  180.10  180.93
 -829.92 -829.84 -829.96 -829.84 -830.04 -830.02 -830.37 -830.15 -830.56 -830.47
 -834.21 -841.48 -837.56 -830.20 -829.94 -830.04 -829.94 -830.09 -829.01 -828.65
 -828.47 -828.35 -828.11 -827.76 -827.38 -827.00 -826.88  165.62  167.22  166.57
  166.13 -826.37 -826.48 -826.00 -825.98 -825.14 -824.87 -824.06 -824.00 -824.30
 -824.07 -823.43 -823.47 -823.19 -823.15 -822.65 -821.86 -821.58 -821.65 -821.29
 -821.21 -820.96 -821.07 -820.71 -820.70 -820.33 -820.50 -819.96 -819.90 -819.07
 9330.21 9334.12 9344.68 9355.25 9365.81 9384.78 9429.18 9471.43 9492.55 9540.13
 9545.36 9555.92 9566.49 9571.20 9577.05 9587.61 9602.27 9619.30 9629.86 9650.98
 9661.54 9714.35 9724.92 9767.16 9788.29 9813.53 9813.5310299.0610300.5310300.53
10305.8310316.8810337.5110348.0710390.1210447.4210481.0810505.3210536.7410568.16
10620.5210631.0010662.4210682.9910704.3110756.6710788.0910798.5710817.6110840.46
10851.2610871.8810892.8210913.7710945.1910966.1310976.6110997.5511018.5011085.16
  170.08  170.02  170.16  170.04  170.16  169.96  169.98  169.63  169.85  169.44
  169.53  165.79  158.52  162.44  169.80  170.06  169.96  170.06  169.91  170.99
  171.35  171.89  172.24  172.62  173.00  173.07  173.07  174.72  174.58  174.58
  174.07  173.52  174.00  174.02  174.74  175.13  175.94  176.00  175.70  175.93
  176.57  176.53  176.81  176.85  177.35  178.14  178.42  178.35  178.71  178.79
  179.04  178.93  179.29  179.30  179.67  179.50  179.76  180.04  180.10  180.93
 -829.92 -829.98 -829.84 -829.96 -829.84 -830.04 -830.02 -830.37 -830.15 -830.56
 -830.47 -834.21 -841.48 -837.56 -830.20 -829.94 -830.04 -829.94 -830.09 -829.01
 -828.65 -828.11 -827.76 -827.38 -827.00 -826.93  165.57  167.22  167.08 -825.42
 -825.93 -826.48 -826.00 -825.98 -825.26 -824.87 -824.06 -824.00 -824.30 -824.07
 -823.43 -823.47 -823.19 -823.15 -822.65 -821.86 -821.58 -821.65 -821.29 -821.21
 -820.96 -821.07 -820.71 -820.70 -820.33 -820.50 -820.24 -819.96 -819.90 -819.07
Pier Skew, UpSta & Num, DnSta & Num=  ,9923.52, 2 ,9909.73, 2 , 0 , 0 , 0 ,,
    4.00    4.00
 -826.56  173.44
    4.00    4.00
 -826.60  173.40
Pier Skew, UpSta & Num, DnSta & Num=  ,10021.72, 2 ,10007.93, 2 , 0 , 0 , 0 ,,
    4.00    4.00
 -826.22  173.78
    4.00    4.00
 -826.27  173.73
Pier Skew, UpSta & Num, DnSta & Num=  ,10119.92, 2 ,10106.13, 2 , 0 , 0 , 0 ,,
    4.00    4.00
 -825.89  174.11
    4.00    4.00
 -825.94  174.06
Pier Skew, UpSta & Num, DnSta & Num=  ,10218.12, 2 ,10204.33, 2 , 0 , 0 , 0 ,,
    4.00    4.00
 -825.56  174.44
    4.00    4.00
 -825.60  174.40
BR Coef=-1 , 0 , 0 ,, 0 ,,,0.8,0,1,0,
WSPro=,,,, 1 ,,,, 0 ,,,, 0 ,,,,-1 ,-1 ,-1 , 0 , 0 , 0 , 0 , 0
BC Design=,, 0 ,, 0 ,,,,,,

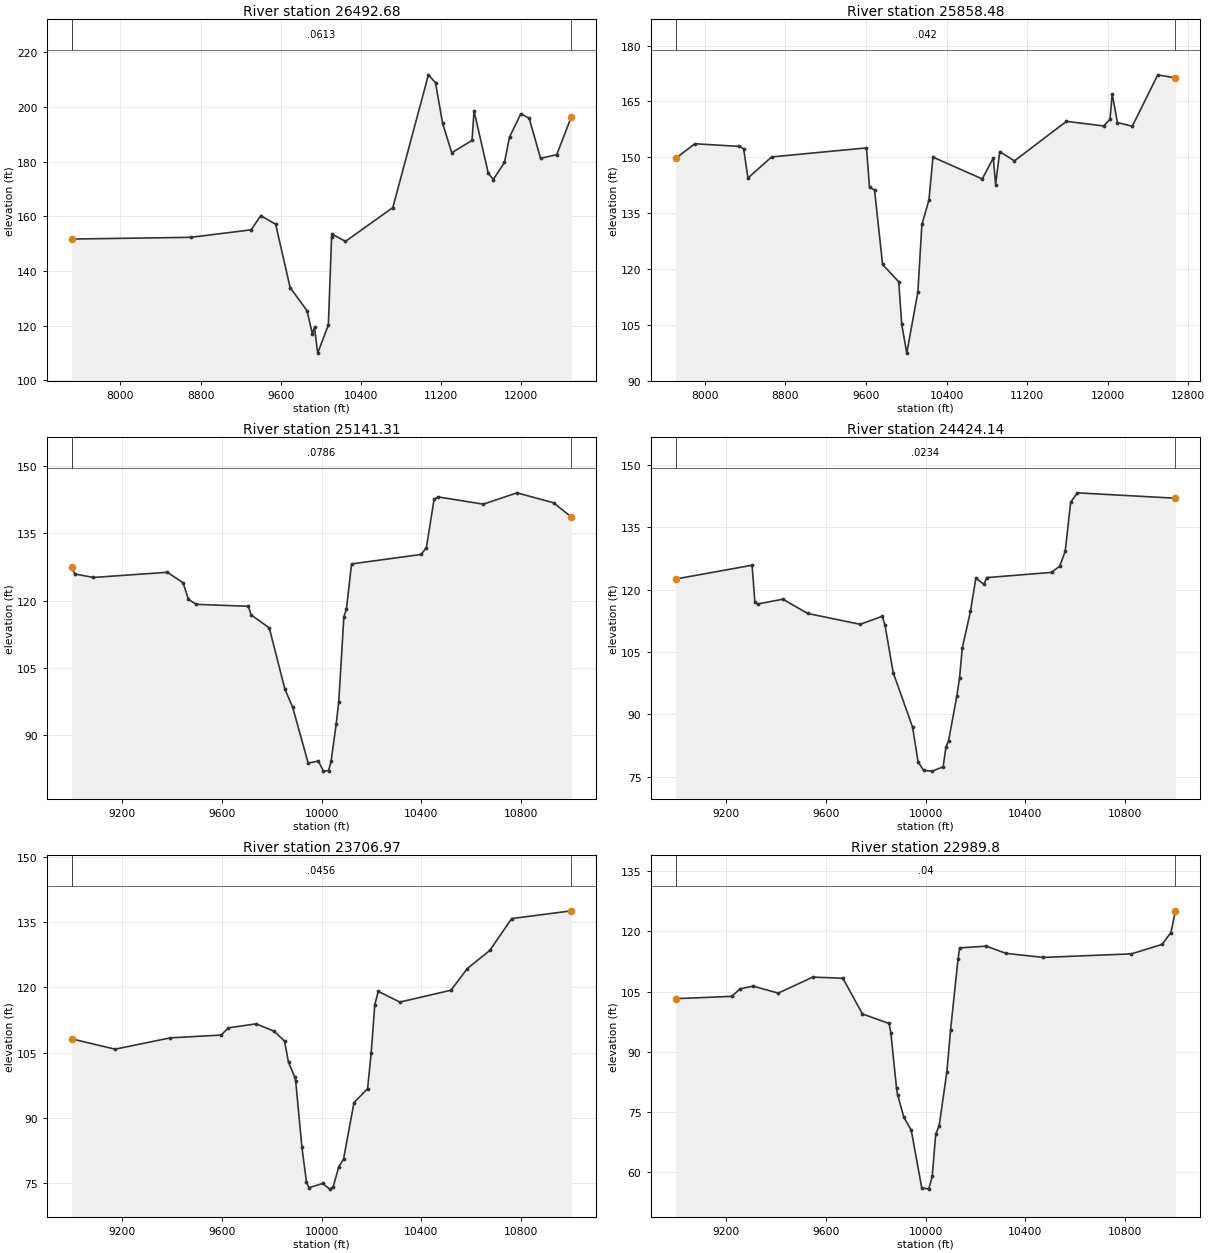
Type RM Length L Ch R = 1 ,26492.68,634.202200,634.202200,634.202200
XS GIS Cut Line= 6
 673231.65177229720447.811702326671834.332287192721198.614036486
671441.646325529721343.342718944670717.124239564721583.527884379
669107.752744913721863.145626798668561.499688327722051.492567569
#Sta/Elev= 30
7514.301151.6902 8701.22152.31859304.186155.06419399.853160.22589549.025157.1127
9693.791133.9317 9862.09125.49019915.293117.01149936.574119.44949968.496109.9556
 10074.9120.272910106.82152.326510114.19153.456310245.15  150.8310717.88163.2015
11072.82211.765411143.63 208.86111214.44194.036111305.48183.262211507.79187.7775
11528.02198.570111669.63175.826111720.21 173.46611831.48179.752711882.05189.0041
11994.98197.534912077.72195.8801 12191.5181.223912352.85182.5605 12499.6196.5165
#Mann= 3 , 0 , 0
7514.301  0.0613       07514.301  0.0613       0 12499.6  0.0613       0
#XS Ineff= 2 , 0
       09804.667        10308.54       0
Bank Sta=7514.301,12499.6
Exp/Cntr=0.3,0.1

Type RM Length L Ch R = 1 ,25858.48,717.170300,717.170300,717.170300
XS GIS Cut Line= 6
673171.958675385  720241.0567431672376.994525284720558.538393185
671498.522303075720849.337004319670679.077858597720863.225893199
670022.827858627720998.642559871 668418.66119194721533.364782095
#Sta/Elev= 30
7710.517149.68667901.066 153.6248342.553152.91868385.625152.31958428.697144.4198
8663.436150.08399605.424152.51789635.428141.97439685.435141.17939765.447121.2067
 9925.47116.56619955.474105.104310005.4897.39669 10115.5113.7917 10155.5131.9465
10225.51138.514810265.52150.031710754.67144.180610864.53149.786210887.41142.6798
10928.25 151.523 11074.1149.022911590.61159.645511959.54158.402812022.79160.1768
12045.18166.963212096.57159.333512244.14158.314312497.13172.136412672.46171.3056
#Mann= 3 , 0 , 0
7710.517   0.042       07710.517   0.042       012672.46   0.042       0
#XS Ineff= 2 , 0
       0                10699.11       0
Bank Sta=7710.517,12672.46
Exp/Cntr=0.3,0.1

Type RM Length L Ch R = 1 ,25141.31,717.170300,717.170300,717.170300
XS GIS Cut Line= 6
671746.819436619719882.648059269671431.857862757719995.033810133
670942.898389394720145.660319752670655.394157828720212.070701027
670324.956788141720298.694190793669826.442405942720443.183474412
#Sta/Elev= 30
8999.031127.52799011.657 125.9259086.429125.14279382.633126.29829445.581123.9401
9466.564120.28639498.038119.16219707.118118.73219717.564116.8288 9790.69113.9105
9853.296100.26189884.35896.239729946.38683.843359987.22184.2660210007.6282.03681
   1002882.1612510038.1984.2057110058.5792.5024210068.8397.4271210089.36116.4004
10099.63118.094810120.17128.156310399.16 130.26910419.84131.796210450.85142.5546
10467.34143.064310647.93141.459710782.91143.9815 10929.3141.765411000.98138.5902
#Mann= 3 , 0 , 0
8999.031  0.0786       08999.031  0.0786       011000.98  0.0786       0
#XS Ineff= 2 , 0
       0                               0
Bank Sta=8999.031,11000.98
Exp/Cntr=0.3,0.1

Type RM Length L Ch R = 1 ,24424.14,717.170400,717.170400,717.170400
XS GIS Cut Line= 6
671566.445820108719041.324663137671206.983366438719227.715069183
670746.563842092719444.707471989670608.994583802719512.374228877
670131.311938115719715.621367377669754.164123879719890.108211103
#Sta/Elev= 30
8999.016122.56959305.296125.88859316.504117.04549327.712116.5626 9428.36117.7078
9528.308114.27259738.248111.67269826.462113.59119837.488111.53989870.568100.0491
9948.12986.92116 9970.4278.54817 9992.7176.51069 10026.876.3428610070.6477.38011
10081.5882.0535510092.5383.7076810125.37 94.390310136.31 98.763110147.26 105.992
10179.99114.783210201.63122.7924 10234.1121.262710244.93122.904410505.12124.1658
10537.81125.6856 10559.6129.2824 10581.4141.047410608.11 143.30711000.98  142.01
#Mann= 3 , 0 , 0
8999.016  0.0234       08999.016  0.0234       011000.98  0.0234       0
#XS Ineff= 2 , 0
       0                               0
Bank Sta=8999.016,11000.98
Exp/Cntr=0.3,0.1

Type RM Length L Ch R = 1 ,23706.97,717.170300,717.170300,717.170300
XS GIS Cut Line= 6
670971.925583476718248.422024314670771.203336446718406.814346969
670562.118490536718589.663986588669890.986840221719263.827874913
669718.025465121719406.348534027669479.046892037719575.481676239
#Sta/Elev= 30
8999.019108.18359172.922105.81019394.157108.41619597.719109.05549627.031110.7147
9738.157111.63249810.102109.92889851.741107.66649867.658102.79179893.46499.32079
9896.43698.486649921.27983.274939939.60375.273879949.09473.9707310004.7474.95239
10032.5373.6475710046.4274.1445510069.1578.8277210088.1180.56582 10129.893.51433
10184.3696.7328110198.76104.956310213.18116.041710227.07119.092910313.56 116.635
10518.23119.358510584.11124.344610673.65128.496610761.54135.825411000.97137.6052
#Mann= 3 , 0 , 0
8999.019  0.0456       08999.019  0.0456       011000.97  0.0456       0
#XS Ineff= 2 , 0
       0                               0
Bank Sta=8999.019,11000.97
Exp/Cntr=0.3,0.1

Type RM Length L Ch R = 1 , 22989.8,717.170300,717.170300,717.170300
XS GIS Cut Line= 6
670468.524367519717845.351851633669956.351947308718224.007695207
669776.912228178718376.787193854669537.996702148718601.783442698
669333.335820994718771.482719351668900.223333429719085.425431813
#Sta/Elev= 30
 8999.02103.22299223.934103.80289258.031105.6922 9310.05 106.3459409.687104.6031
9548.421108.59269669.024108.31199747.38599.418419853.89797.056619861.07494.79653
9883.85380.973059888.10579.334459913.173 73.71229942.88570.477569984.92456.15388
 10012.955.8205310026.8458.9693410040.7869.4686610054.7171.6011610085.6385.08058
10100.4895.5488210130.29113.075810136.67115.872710243.41116.2989 10322.2114.4999
 10471.7113.4953 10824.7114.376410947.63116.729710982.98119.679411000.97125.0886
#Mann= 3 , 0 , 0
 8999.02    0.04       0 8999.02    0.04       011000.97    0.04       0
#XS Ineff= 2 , 0
       0                               0
Bank Sta=8999.02,11000.97
Exp/Cntr=0.3,0.1

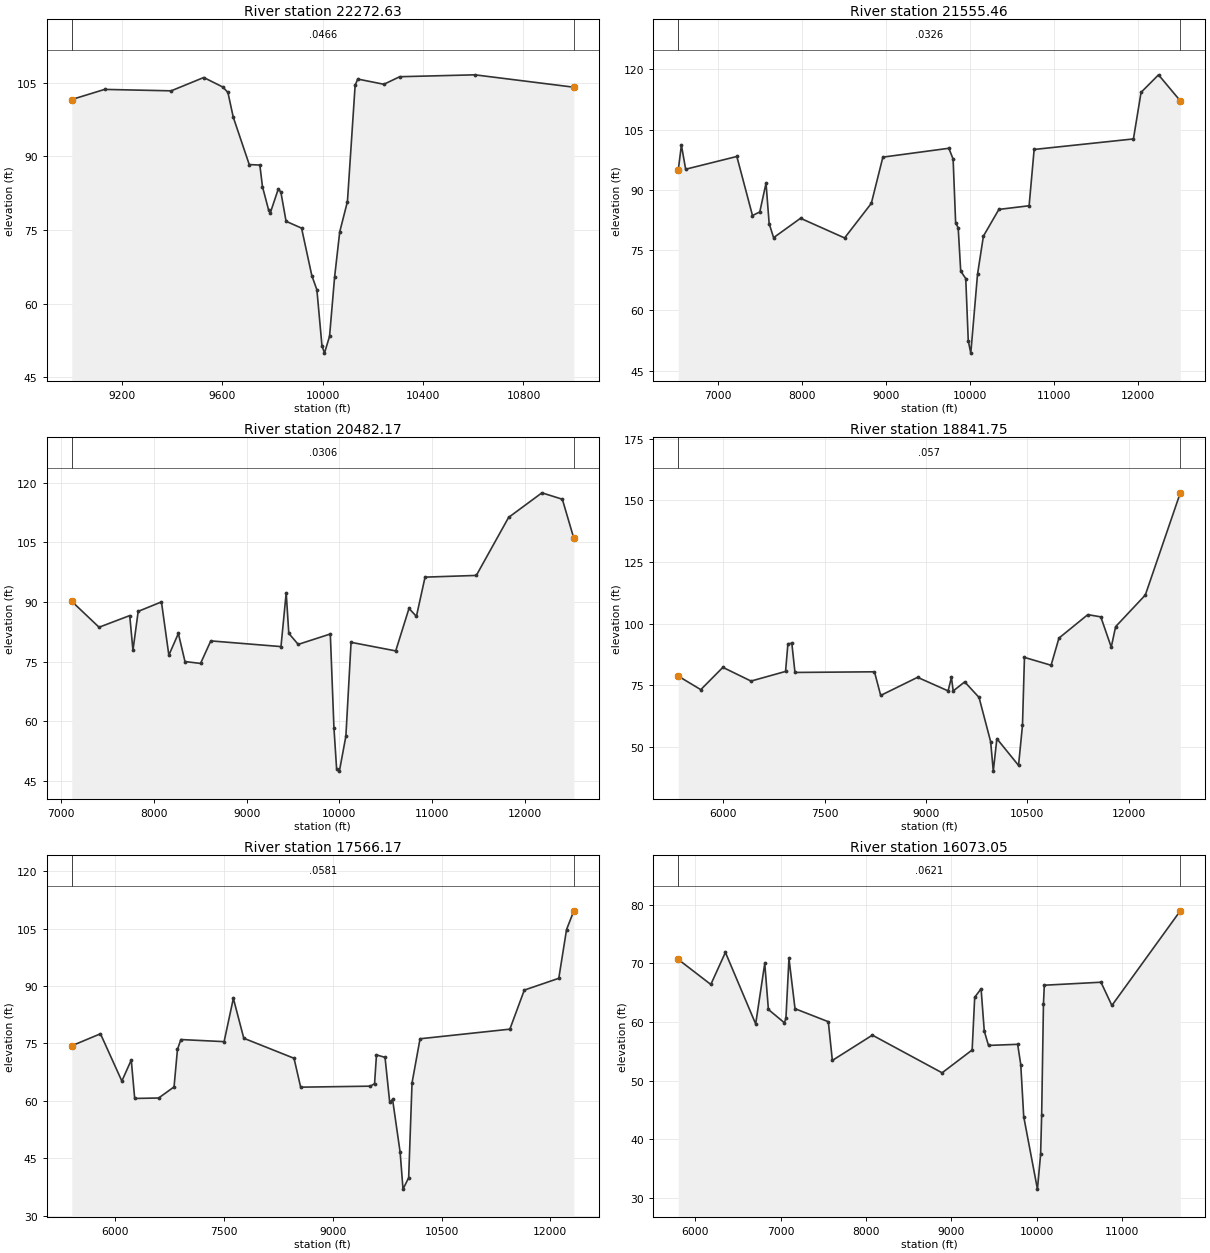
Type RM Length L Ch R = 1 ,22272.63,717.170300,717.170300,717.170300
XS GIS Cut Line= 6
670271.487322198717485.050239986 669761.39756234717721.457682488
669493.178975984 717813.12880148669216.478926481717867.558748185
668992.998323748717936.947320191668409.978524646718198.157657037
#Sta/Elev= 30
8999.084101.60219130.073103.66249395.411103.3702 9525.33106.08719601.285 104.147
 9621.62103.04999642.89898.010549706.73388.343199748.94188.244369759.41883.84318
9784.35678.989869790.84878.528539822.27983.331579832.75682.754379853.559 76.7797
9915.31875.390899956.10265.731299976.33662.835389996.57151.4613110006.6749.91289
10026.8953.34829 10047.165.4425610067.4874.6344710098.1880.7954110128.91104.4963
 10139.3105.770910243.45104.705910306.66106.247410606.61106.632511000.92104.1079
#Mann= 3 , 0 , 0
8999.084  0.0466       08999.084  0.0466       011000.92  0.0466       0
#XS Ineff= 2 , 0
       0                               0
Bank Sta=8999.084,11000.92
Exp/Cntr=0.3,0.1

Type RM Length L Ch R = 1 ,21555.46,1073.291300,1073.291300,1073.291300
XS GIS Cut Line= 6
672207.334933043715442.715793088670108.629789025716899.431403473
669636.761293769717088.755730599668932.996632785717170.413348496
668558.767439723717328.404577166667135.408243686718414.565684661
#Sta/Elev= 30
6523.01294.881576560.647101.15436611.31295.15324 7220.8398.326947406.96983.62031
7493.83484.51452 7568.2991.675937605.51881.619527658.394 78.10897979.07682.93875
8503.71978.038438821.953 86.65328959.51798.163719745.091100.37019795.79897.67733
9825.98481.733699856.13680.596189886.27869.789219946.30967.918829976.31552.39311
10006.3249.3583210086.3468.9651510156.4678.4949510340.5985.1442910700.6886.05713
10760.52100.074811942.64102.6949 12033.6114.292912241.51118.658412500.87112.1744
#Mann= 3 , 0 , 0
6523.012  0.0326       06523.012  0.0326       012500.87  0.0326       0
#XS Ineff= 2 , 0
       09503.509                       0
Bank Sta=6523.012,12500.87
Exp/Cntr=0.3,0.1

Type RM Length L Ch R = 1 ,20482.17,1640.412800,1640.412800,1640.412800
XS GIS Cut Line= 6
670833.145784974714587.277245715669799.846495956715154.578816131
668254.253371209716731.714657769668089.045009702716991.451711029
667791.444580019717361.035959303666905.920782864718238.775255039
#Sta/Elev= 30
7112.23790.134027406.72983.629817737.56186.559877772.42877.828177828.82587.61888
8079.80189.994268159.65776.615978262.328 82.06518333.61875.015138501.63574.53075
8612.26680.199639369.48678.768219425.729 92.28599453.73282.093659555.21979.31962
9901.77881.932599940.97358.328269969.54748.121179999.78847.4743410069.7956.26973
 10125.879.8406510607.45 77.684110750.6488.3599810830.6886.3570910923.9896.22232
11477.1396.6497711825.65111.235412184.94117.405112405.07115.797412529.32105.9619
#Mann= 3 , 0 , 0
7112.237  0.0306       07112.237  0.0306       012529.32  0.0306       0
#XS Ineff= 2 , 0
       09424.588                       0
Bank Sta=7112.237,12529.32
Exp/Cntr=0.3,0.1

Type RM Length L Ch R = 1 ,18841.75,1275.589000,1275.589000,1275.589000
XS GIS Cut Line= 4
670872.208285004713128.943912357668847.695151031 714325.24712792
667057.104118347715863.318912372665077.937451631717725.298079044
#Sta/Elev= 30
5332.71678.71725 5666.3273.222625993.29582.263146409.70576.700596920.78280.60556
6955.62891.820097013.70592.000597060.16780.194858236.38180.460468328.46470.87109
8874.26478.22183 9326.0272.719589375.20778.164349401.57272.698569571.57376.36553
9783.87170.065779955.24952.164549994.79440.1769410047.6453.3410410368.27 42.4959
10426.6558.7444710455.8386.2974510849.8783.1148710966.6294.1332211393.16103.6377
11585.38102.7351 11740.1 90.469611805.0698.7703212244.41111.598712762.11 153.037
#Mann= 3 , 0 , 0
5332.716   0.057       05332.716   0.057       012762.11   0.057       0
#XS Ineff= 2 , 0
       09284.449                       0
Bank Sta=5332.716,12762.11
Exp/Cntr=0.3,0.1

Type RM Length L Ch R = 1 ,17566.17,1493.114200,1493.114200,1493.114200
XS GIS Cut Line= 4
669810.426707894712305.065233275668058.421174467713403.329590529
665090.958284974715902.381412372664348.770784974716540.402245715
#Sta/Elev= 30
5398.44874.405515794.33177.535496089.38965.193086219.21570.691236266.42560.65532
6596.89160.772636809.33363.669896856.54273.470766903.75276.030947499.868 75.4824
7627.58486.771957771.39576.369568464.30171.141388555.81763.602429518.01263.86352
9575.56664.522289601.71472.022029719.82771.384369784.74659.602859823.96760.41138
9928.55746.565529967.77836.9883410045.8339.9575510092.4164.72959 10203.1 76.2329
11441.8678.7423211641.2888.9391312116.8292.0163212224.01104.745712324.53109.6277
#Mann= 3 , 0 , 0
5398.448  0.0581       05398.448  0.0581       012324.53  0.0581       0
#XS Ineff= 2 , 0
       09114.252                       0
Bank Sta=5398.448,12324.53
Exp/Cntr=0.3,0.1

Type RM Length L Ch R = 1 ,16073.05,2308.691200,2308.691200,2308.691200
XS GIS Cut Line= 6
668432.554839492711651.246262789666573.942683041712823.727098688
665839.690322727713452.232424587665482.206353098713727.002781227
664591.951785743714357.426844537663677.736045599715100.005784333
#Sta/Elev= 30
5799.54170.660956181.42866.387856352.355 71.8592 6707.0659.653126813.47269.97825
6856.16162.120777043.58759.847617061.766 60.63897097.23670.826057168.17762.25151
7558.353 60.03167605.647 53.4255  8074.757.739358891.82151.313219244.02855.20808
9273.83564.198129348.70165.658849386.13458.427929435.69955.986169777.21756.17321
9813.59152.728739848.36443.8294410009.1731.4674510046.2837.4146510058.6544.13336
10079.6463.0345210089.5866.2571410753.6866.7683410881.5662.7983911683.4978.94903
#Mann= 3 , 0 , 0
5799.541  0.0621       05799.541  0.0621       011683.49  0.0621       0
#XS Ineff= 2 , 0
       0 8721.81                       0
Bank Sta=5799.541,11683.49
Exp/Cntr=0.3,0.1

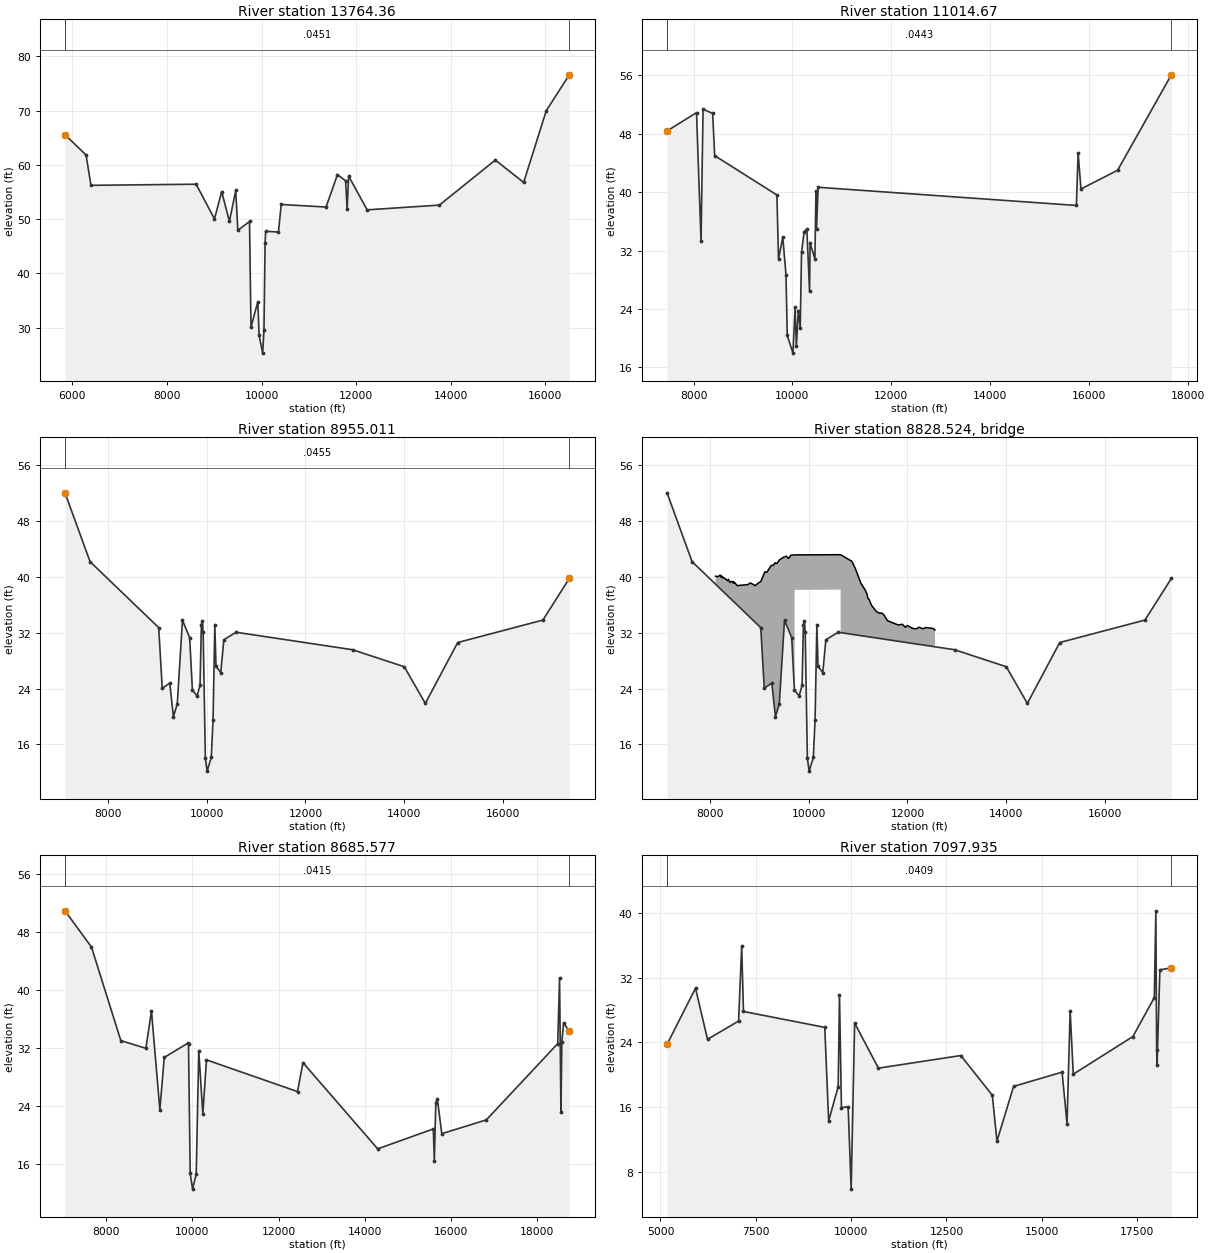
Type RM Length L Ch R = 1 ,13764.36,2749.686400,2749.686400,2749.686400
XS GIS Cut Line= 5
667151.599782318710208.384720191666191.578218848710757.321876422
663039.741019875  712708.4591901662106.854508668713860.848409757
659190.187842011717110.848409772
#Sta/Elev= 30
 5845.2865.570216290.617  61.8276394.29156.240358617.20456.450229005.31850.05431
9158.21255.081369321.57549.596399454.56555.289489499.282 47.94059746.26449.57601
9777.54130.126929922.67934.790719948.52928.6074510024.5225.3083110052.05 29.5797
10075.5745.5288710087.3347.7765910357.8447.6248810416.6452.7135511364.8952.24123
11605.6858.2311811778.1157.07754 11809.9 51.803911841.6857.9459712233.3251.72265
13760.4752.5981614943.2660.9042115542.1556.7751916021.2570.0199516507.5776.61396
#Mann= 3 , 0 , 0
 5845.28  0.0451       0 5845.28  0.0451       016507.57  0.0451       0
#XS Ineff= 2 , 0
       0 8674.18        11148.62       0
Bank Sta=5845.28,16507.57
Exp/Cntr=0.3,0.1

Type RM Length L Ch R = 1 ,11014.67,2059.662500,2059.662500,2059.662500
XS GIS Cut Line= 6
665268.662759364 709193.94903858 663849.39192602709480.407371908
661979.408747315710251.775433123661648.521175325710527.515076429
660440.607127696712590.260604069658481.854508698715965.015076429
#Sta/Elev= 30
7465.18348.382128060.61550.88941 8152.4333.338758193.23751.366658387.06850.78578
8427.87545.002659685.85839.61032 9718.31 30.83119804.84933.846629869.754 28.6586
9895.40320.3614610010.3817.9426110053.6524.2198410078.9718.9182910118.5523.77273
10157.6421.3880810183.4631.7333210237.5434.6000810291.6334.9041910345.7226.42117
10356.5433.0038310453.8930.8823710475.5340.1800310486.3434.98842 10518.840.66724
15739.66 38.175515774.3545.3917215832.1640.4382916572.1542.9933417659.03 56.0734
#Mann= 3 , 0 , 0
7465.183  0.0443       07465.183  0.0443       017659.03  0.0443       0
#XS Ineff= 2 , 0
       0                13570.09       0
Bank Sta=7465.183,17659.03
Exp/Cntr=0.3,0.1

Type RM Length L Ch R = 1 ,8955.011,269.433700,269.433700,269.433700
XS GIS Cut Line= 6
664567.273870468708351.067094117662564.627426118707751.195055023
659880.207898229709356.709455237659528.907128781709612.522431672
658648.521175355710798.348409772657211.021175325713485.848409772
#Sta/Elev= 30
  7136.152.018667642.30942.169079031.85732.714359102.97424.030239255.23424.78172
9328.73819.969959407.09121.783439512.22433.764749657.64131.302939713.145 23.7757
9807.55222.930389867.43524.44865 9894.8633.148959913.03233.696869931.20332.04234
9975.22513.9887110011.1612.1699710094.9914.1258410131.0919.5467710166.8533.14953
 10190.8 27.187310286.6226.2732410349.1530.9729210598.0132.0546412953.4229.55237
13999.6227.1152214424.9221.8688315080.29 30.583416804.0733.8000817338.0439.75839
#Mann= 3 , 0 , 0
  7136.1  0.0455       0  7136.1  0.0455       017338.04  0.0455       0
#XS Ineff= 2 , 0
       0                15341.03       0
Bank Sta=7136.1,17338.04
Exp/Cntr=0.3,0.1

Type RM Length L Ch R = 3 ,8828.524,,,
BEGIN DESCRIPTION:
END DESCRIPTION:
Bridge Culvert--1,0,-1,-1, 0
Deck Dist Width WeirC Skew NumUp NumDn MinLoCord MaxHiCord MaxSubmerge Is_Ogee
105.716850,58.000000,2.6,0, 60, 60, , , 0.95, 0, 0,0,,
 8117.42 8160.85 8209.01 8225.01 8237.23 8257.09 8265.45 8364.03 8378.33 8406.81
 8449.58 8470.97 8481.66 8492.36 8503.05 8556.52 8770.40 8822.92 8914.22 9034.76
 9115.12 9156.87 9240.43 9292.65 9320.25 9360.75 9409.01 9493.47 9553.79 9581.84
 9614.12 9638.25 9717.23 9717.2310647.2310647.2310874.4610943.7911059.3411151.78
11184.5811196.5411227.2311268.1611370.4711442.0811472.7811523.9311594.7911815.73
11896.0711956.3211996.4912106.9612187.3012227.4712317.7712367.9112518.3212556.39
   40.09   40.00   40.25   39.96   40.13   39.85   39.95   39.43   39.63   39.19
   39.35   39.13   39.31   39.07   39.17   38.73   38.88   39.12   38.74   39.35
   40.70   40.66   41.59   41.68   42.00   41.91   42.41   42.80   42.95   42.65
   42.75   43.09   43.13   43.13   43.16   43.16   42.22   41.20   39.06   38.01
   37.44   36.97   36.71   35.96   35.02   34.76   34.84   34.54   33.71   33.09
   33.20   32.77   33.02   32.60   32.55   32.78   32.55   32.73   32.60   32.37
 -959.91 -960.00 -959.75 -960.04 -959.87 -960.15 -960.05 -960.57 -960.37 -960.81
 -960.65 -960.87 -960.69 -960.93 -960.83 -961.27 -961.12 -960.88 -961.26 -960.65
 -959.30 -959.34 -958.41 -958.32 -958.00 -958.09 -957.59 -957.20 -957.05 -957.35
 -957.25 -956.91 -956.87   38.13   38.16 -956.84 -957.78 -958.80 -960.94 -961.99
 -962.56 -963.03 -963.29 -964.04 -964.98 -965.24 -965.16 -965.46 -966.29 -966.91
 -966.80 -967.23 -966.98 -967.40 -967.45 -967.22 -967.45 -967.27 -967.40 -967.63
 8117.42 8160.85 8209.01 8225.01 8237.23 8257.09 8364.03 8378.33 8406.81 8449.58
 8470.97 8481.66 8492.36 8503.05 8556.52 8770.40 8822.92 8914.22 9034.76 9115.12
 9156.87 9240.43 9292.65 9320.25 9360.75 9409.01 9493.47 9553.79 9581.84 9661.40
 9661.4010591.4010591.4010656.1610687.9010839.8010874.4610943.7911059.3411151.78
11184.5811196.5411227.2311268.1611370.4711442.0811472.7811523.9311594.7911815.73
11896.0711956.3211996.4912106.9612187.3012227.4712317.7712367.9112518.3212556.39
   40.09   40.00   40.25   39.96   40.13   39.85   39.43   39.63   39.19   39.35
   39.13   39.31   39.07   39.17   38.73   38.88   39.12   38.74   39.35   40.70
   40.66   41.59   41.68   42.00   41.91   42.41   42.80   42.95   42.65   43.13
   43.13   43.16   43.16   43.16   42.86   42.48   42.22   41.20   39.06   38.01
   37.44   36.97   36.71   35.96   35.02   34.76   34.84   34.54   33.71   33.09
   33.20   32.77   33.02   32.60   32.55   32.78   32.55   32.73   32.60   32.37
 -959.91 -960.00 -959.75 -960.04 -959.87 -960.15 -960.57 -960.37 -960.81 -960.65
 -960.87 -960.69 -960.93 -960.83 -961.27 -961.12 -960.88 -961.26 -960.65 -959.30
 -959.34 -958.41 -958.32 -958.00 -958.09 -957.59 -957.20 -957.05 -957.35 -956.87
   38.13   38.16 -956.84 -956.84 -957.14 -957.52 -957.78 -958.80 -960.94 -961.99
 -962.56 -963.03 -963.29 -964.04 -964.98 -965.24 -965.16 -965.46 -966.29 -966.91
 -966.80 -967.23 -966.98 -967.40 -967.45 -967.22 -967.45 -967.27 -967.40 -967.63
BR Coef=-1 , 0 , 0 ,, 0 ,,,0.8,0,1,0,
WSPro=,,,, 1 ,,,, 0 ,,,, 0 ,,,,-1 ,-1 ,-1 , 0 , 0 , 0 , 0 , 0
BC Design=,, 0 ,, 0 ,,,,,,

Type RM Length L Ch R = 1 ,8685.577,1587.641900,1587.641900,1587.641900
XS GIS Cut Line= 6
 664497.82942605707392.733760789662411.849648327707542.167277217
  661013.9329817708467.167277217659164.062064946708976.935149685
656863.714842707710571.987233028655497.960759401713476.889499456
#Sta/Elev= 30
7038.68550.858947653.63945.862768335.99632.956568917.87331.892689047.88437.03978
9242.75623.411639344.92930.632979896.62532.620359908.55332.454089948.00614.64608
10003.0412.4692110087.4714.5379310147.1131.5458910241.5422.8211910326.0230.29954
12441.8125.9245112568.0729.9194614305.4618.0236615597.6620.77213 15620.9 16.3599
15655.7524.40077 15690.624.9174215795.1620.1191416829.1122.0174518488.4132.53752
18531.19  41.61718563.2723.1487718584.6632.8211718625.0335.4302618757.7834.21991
#Mann= 3 , 0 , 0
7038.685  0.0415       07038.685  0.0415       018757.78  0.0415       0
#XS Ineff= 2 , 0
       0                16199.48       0
Bank Sta=7038.685,18757.78
Exp/Cntr=0.3,0.1

Type RM Length L Ch R = 1 ,7097.935,743.697300,743.697300,743.697300
XS GIS Cut Line= 6
664670.863767207704645.479290605 660118.92317602 707240.82403858
658013.888453811709031.188621908656679.253037125710474.330983013
655713.696909292712054.331919481655260.008477032713379.406732246
#Sta/Elev= 30
5172.70423.75507 5919.2430.700596233.96824.379697049.13926.638257130.42735.93296
7176.87727.822149309.076 25.85619411.14614.28446 9660.6518.538449694.67329.87732
9746.534 15.93349921.49516.0488710000.92 5.8574310091.6126.3884310715.7620.81552
12876.0922.3753213702.2717.4693413824.8611.7953414260.7318.56335 15532.720.32066
15661.6113.9588815743.6527.8897815825.6820.0677417388.6424.7208717949.8329.52955
17991.1240.2663618012.2623.0714218022.8321.2396818096.8232.9683718397.4433.21889
#Mann= 3 , 0 , 0
5172.704  0.0409       05172.704  0.0409       018397.44  0.0409       0
#XS Ineff= 2 , 0
       0                15826.76       0
Bank Sta=5172.704,18397.44
Exp/Cntr=0.3,0.1

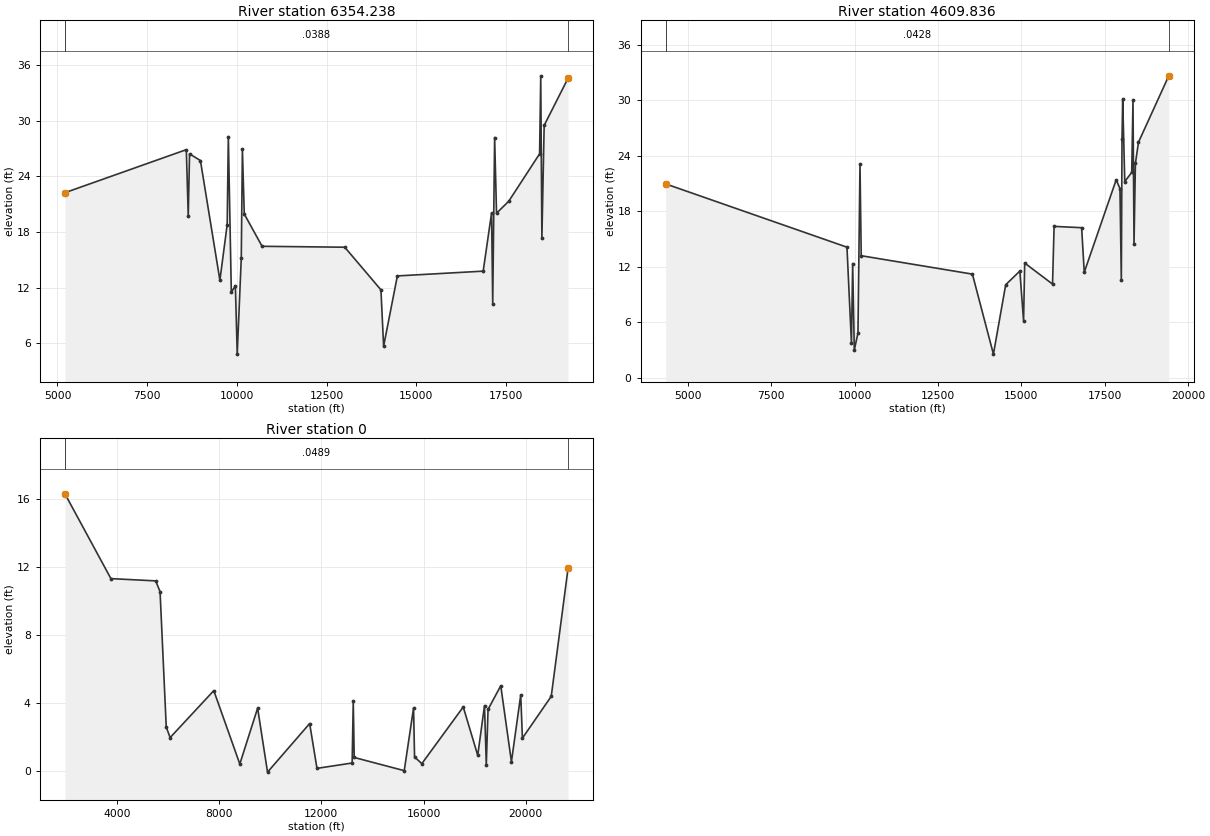
Type RM Length L Ch R = 1 ,6354.238,1744.402300,1744.402300,1744.402300
XS GIS Cut Line= 6
 664504.19710055704103.812623948660874.491833925706136.518715754
659634.400084585706598.419197395657434.752656132708381.590401709
655990.308211654710506.590401724654947.508477062713431.490065575
#Sta/Elev= 30
5208.84322.232598589.86526.870748643.54119.70176 8679.7526.418878982.72125.69629
9525.27812.798259728.59118.798569760.04928.274099843.42411.515769956.70312.18074
10007.814.83060410120.6915.1801510151.75 26.902210203.9419.9354710700.6516.45442
13002.9916.3546914011.29 11.757914085.775.68302314468.8313.2607716859.6513.77546
17093.21 20.057217125.0610.2830117178.1428.1794917231.2220.0213917570.9521.30661
18430.8926.4218218462.7434.8298618494.5917.3247118558.2929.4882119223.4134.57336
#Mann= 3 , 0 , 0
5208.843  0.0388       05208.843  0.0388       019223.41  0.0388       0
#XS Ineff= 2 , 0
       0                16491.51       0
Bank Sta=5208.843,19223.41
Exp/Cntr=0.3,0.1

Type RM Length L Ch R = 1 ,4609.836,4609.835700,4609.835700,4609.835700
XS GIS Cut Line= 6
664557.519399256703920.237518877660588.769399285 704659.82085219
658734.602732599705430.654185534656609.602732599708274.404185548
655192.936065912711138.987518862654666.258477032713337.740065575
#Sta/Elev= 30
4337.43520.948259771.079 14.10269905.2323.7065569941.65612.334379990.6032.966461
10100.364.82387210161.3423.0810510197.9313.1795113529.9111.1889214160.042.534802
14528.1910.0401814952.1211.5180715063.686.11450915097.1412.3878215931.51 10.1098
15978.4716.3521416804.0216.2094816882.1111.3885117839.1621.3898517952.2720.44584
 17993.410.5038918013.9725.8082418034.5330.0907718096.2321.1992618304.5222.18964
18343.02 30.007418373.8714.44263   1841523.1559618507.5525.4548619415.2632.63733
#Mann= 3 , 0 , 0
4337.435  0.0428       04337.435  0.0428       019415.26  0.0428       0
#XS Ineff= 2 , 0
       0                16629.88       0
Bank Sta=4337.435,19415.26
Exp/Cntr=0.3,0.1

Type RM Length L Ch R = 1 ,       0,0.000000,0.000000,0.000000
XS GIS Cut Line= 6
664861.639271438703091.741799414663540.587450176701880.144931063
660628.671039253702176.495792896658652.976594806701659.829126209
657414.479465276702138.053508699651313.463268161711625.776303589
#Sta/Elev= 30
1971.86116.301043770.01111.319875521.98111.18636 5693.1510.555335934.8012.605842
6085.8331.9788427794.8154.7393818812.6550.4278959509.9683.710113 9897.25-0.04888
11545.162.80531311831.730.17240213207.520.48702113251.244.10883113288.270.812783
 15245.70.03753215610.37 3.7212115649.150.841823 15933.5 0.4488617553.753.779778
   181210.93800818385.683.85825918455.89 0.3733318524.083.63475519021.485.025702
19439.150.55976319803.11 4.4847419868.791.94572120996.424.40322921654.1411.91824
#Mann= 3 , 0 , 0
1971.861  0.0489       01971.861  0.0489       021654.14  0.0489       0
#XS Ineff= 2 , 0
       0                               0
Bank Sta=1971.861,21654.14
Exp/Cntr=0.3,0.1